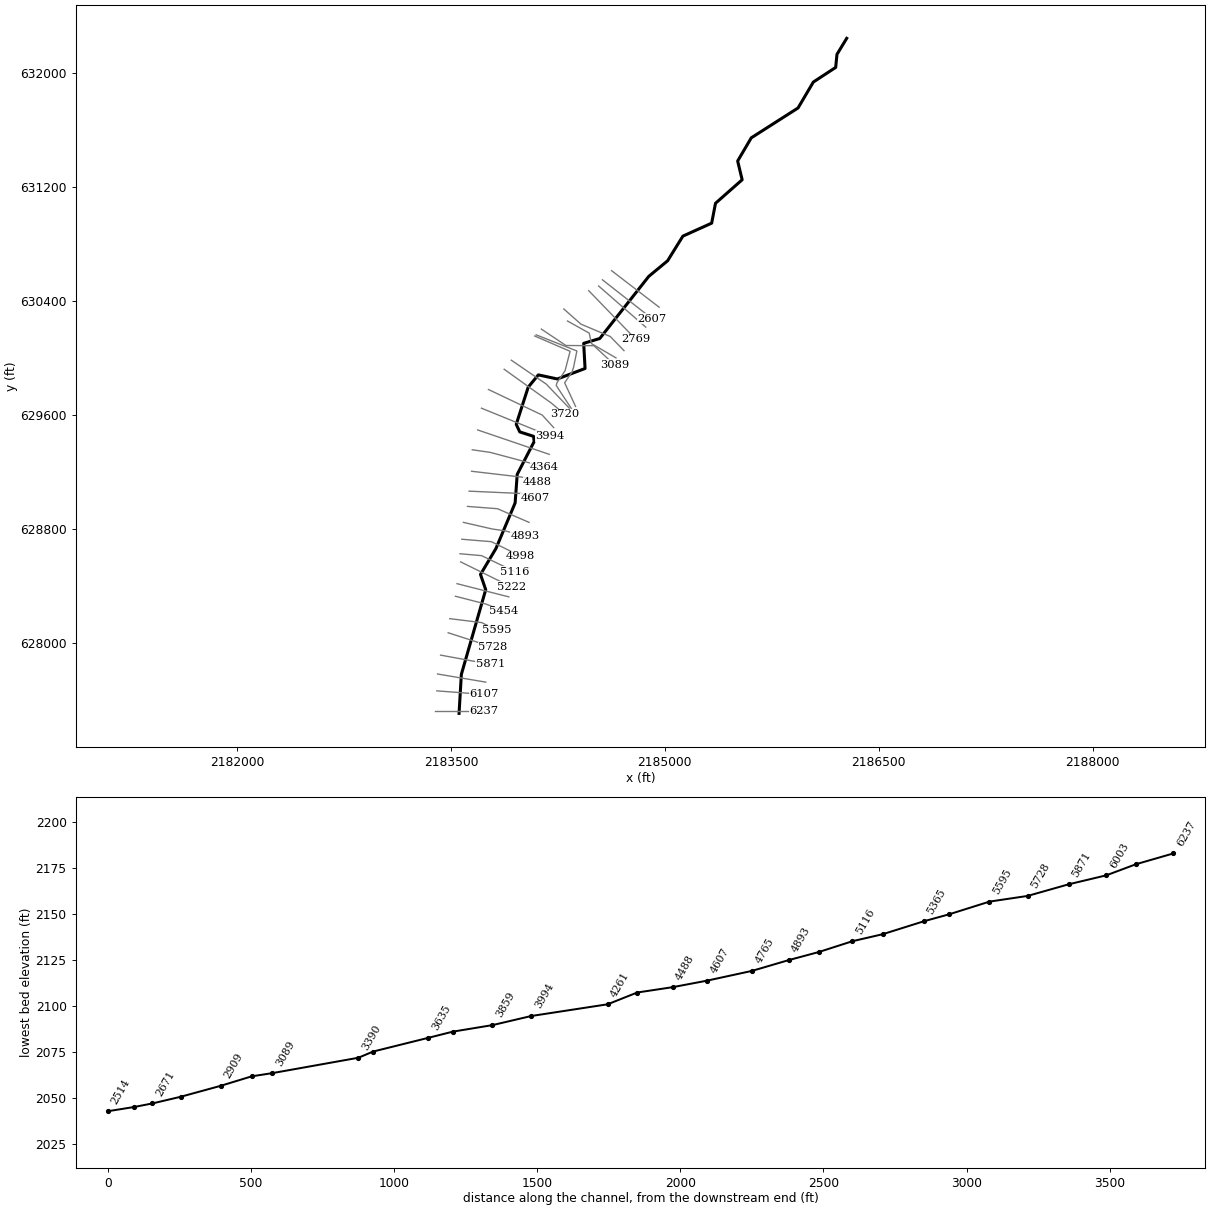
--- SSHANTYRN.prj (project) ---

Proj Title=SSHANTYRN
Current Plan=p01
Default Exp/Contr=0,0
English Units
Geom File=g01
Flow File=f01
Plan File=p01
Background Map Layer=Inundation Boundary (P100yr Value_0)
BEGIN DESCRIPTION:
----------MODEL BY WOOD PLC 2022----------
AFH study
Randolph County, WV
HEC-RAS Version: RAS 6.2
Vertical Datum: NAVD88
Projection: NAD 1983 StatePlane West Virginia S FIPS 4702 (US Feet)
Terrain: 1-meter LIDAR (FEMA Region III 3DEP collected 2016-2018)
Land Use: 2019 NLCD
Hydrologic Method:
WV SIR2010-5033 regression equations
Additional Model Notes:
Several areas appearing unwetted required IFAs to wet channel.
END DESCRIPTION:
DSS Export Rating Curves= 0
DSS Export Rating Curve Sorted= 0
DSS Export Volume Flow Curves= 0
DXF OffsetX= 0
DXF OffsetY= 0
DXF ScaleX= 0
DXF ScaleY= 0

--- SSHANTYRN.p01 (plan) ---

Plan Title=Floodplain
Program Version=6.20
Short Identifier=Floodplain
Geom File=g01
Flow File=f01
Subcritical Flow
K Sum by GR= 0
Std Step Tol= 0.01
Critical Tol= 0.01
Num of Std Step Trials= 20
Max Error Tol= 0.3
Flow Tol Ratio= 0.001
Split Flow NTrial= 30
Split Flow Tol= 0.02
Split Flow Ratio= 0.02
Log Output Level= 0
Friction Slope Method= 1
Unsteady Friction Slope Method= 2
Unsteady Bridges Friction Slope Method= 1
Parabolic Critical Depth
Global Vel Dist= 0 , 0 , 0
Global Log Level= 0
CheckData=True
Encroach Param=-1 ,0,0, 0
Mapping Interval=1HOUR
Computation Time Step Use Courant=        0
Computation Time Step Use Time Series=    0
Computation Time Step Count To Double=0
Computation Time Step Max Doubling=0
Computation Time Step Max Halving=0
Computation Time Step Residence Courant=0
Run HTab= 0
Run UNet= 0
Run Sediment= 0
Run PostProcess= 0
Run WQNet= 0
Run RASMapper=-1
UNET Theta= 0
UNET Theta Warmup= 0
UNET ZTol= 0
UNET ZSATol= 0
UNET MxIter= 0
UNET Max Iter WO Improvement= 0
UNET MaxInSteps= 0
UNET DtIC= 0
UNET DtMin= 0
UNET MaxCRTS= 0
UNET WFStab= 0
UNET SFStab= 0
UNET WFX= 1
UNET SFX= 1
UNET Gravity=32.174
UNET 1D Methodology=Finite Difference
UNET DSS MLevel= 1
UNET Pardiso=0
UNET DZMax Abort= 0
UNET Use Existing IB Tables= 0
UNET Froude Reduction=False
UNET Froude Limit= 0
UNET Froude Power= 0
UNET D1 Cores= 0
UNET WindReference=Eulerian
UNET WindDragFormulation=Hsu (1988)
UNET D2 Coriolis=0
UNET D2 Cores= 0
UNET D2 Theta= 1
UNET D2 Theta Warmup= 1
UNET D2 Z Tol= 0.01
UNET D2 Volume Tol= 0.01
UNET D2 Max Iterations= 20
UNET D2 Equation= 0
UNET D2 RampUpFraction=0.1
UNET D2 TimeSlices= 1
UNET D2 Turbulence Formulation=Non-Conservative (original)
UNET D2 Eddy Viscosity=0.3
UNET D2 Transverse Eddy Viscosity=0.1
UNET D2 Smagorinsky Mixing=0
UNET D2 BCVolumeCheck=0
UNET D2 Cores=0
UNET D2 SolverType=PARDISO (Direct)
UNET D2 Minimum Iterations= 2147483647
UNET D2 Maximum Iterations= 2147483647
UNET D2 Restart Number= 10
UNET D2 Relaxation Coeff=1.3
UNET D2 SOR Precondition Iterations= 10
UNET D2 ILUT Maximum Fill= 8
UNET D2 ILUT Tolerance=1E-08
UNET D1D2 MaxIter= 0
UNET D1D2 ZTol=0.01
UNET D1D2 QTol=0.1
UNET D1D2 MinQTol=1
Write IC File= 0
Write IC File at Fixed DateTime=0
Write IC File at Sim End=0
Echo Input=False
Echo Parameters=False
Echo Output=False
Write Detailed= 0
HDF Write Warmup=0
HDF Write Time Slices=0
HDF Flush=0
HDF Compression= 1
HDF Chunk Size= 1
HDF Spatial Parts= 1
HDF Use Max Rows=0
HDF Fixed Rows= 1
Calibration Method= 0
Calibration Iterations= 20
Calibration Max Change=0.05
Calibration Tolerance=0.2
Calibration Maximum=1.5
Calibration Minimum=0.5
Calibration Optimization Method= 1
WQ AD Non Conservative
WQ ULTIMATE=-1
WQ Max Comp Step=1HOUR
WQ Output Interval=15MIN
WQ Output Selected Increments= 0
WQ Output face flow=0
WQ Output face velocity=0
WQ Output face area=0
WQ Output face dispersion=0
WQ Output cell volume=0
WQ Output cell surface area=0
WQ Output cell continuity=0
WQ Output cumulative cell continuity=0
WQ Output face conc=0
WQ Output face dconc_dx=0
WQ Output face courant=0
WQ Output face peclet=0
WQ Output face adv mass=0
WQ Output face disp mass=0
WQ Output cell mass=0
WQ Output cell source sink temp=0
WQ Output nsm pathways=0
WQ Output nsm derived pathways=0
WQ Create Restart=0
WQ Fixed Restart=0
WQ System Summary=0
WQ Write To DSS=0
Sorting and Armoring Iterations= 10
XS Update Threshold= 0.02
Bed Roughness Predictor= 0
Hydraulics Update Threshold= 0.02
Energy Slope Method= 1
Volume Change Method= 1
Sediment Retention Method= 0
Sediment TS Multiplier= 1
Warm Up Method= 0
XS Weighting Method= 0
Number of US Weighted Cross Sections= 1
Number of DS Weighted Cross Sections= 1
Upstream XS Weight=0
Main XS Weight=1
Downstream XS Weight=0
Number of DS XS's Weighted with US Boundary= 1
Upstream Boundary Weight= 1
Weight of XSs Associated with US Boundary= 0
Number of US XS's Weighted with DS Boundary= 1
Downstream Boundary Weight= 0.5
Weight of XSs Associated with DS Boundary= 0.5
Percentile Method= 0
Sediment Output Level= 3
Mass or Volume Output= 0
Output Increment Type= 1
Profile and TS Output Increment= 1
Transport Output Increment 1
XS Output Flag= 0
XS Output Increment= 10
Read HDF5 Sediment Hotstart= 0
Sediment Hotstart Type= 0
Write Gradation File= 0
Read Gradation Hotstart= 0
Write HDF5 File= 1
Write Binary Output= 1
Write DSS Sediment File= 0
DSS Sediment Output Type= 1
SV Curve= 0
Specific Gage Flag= 0
Subcell Erosion Methods= 0
Subcell Deposition Methods= 0
Advection Scheme= 1
Matrix Solver= 0
Implicit Weighting Factor= 1
Maximum Outer Loop Convergence Iterations= 5
Convergence Maximum Absolute= 0.001
Convergence RMSE= 0.0001
Grain Fractions Max Abs Error= 0.001
Max Subgrid Regions= 1
Max Subgrid Length Scale= 3.402823E+38
Initial Layer Thickness= 3.402823E+38
Min Layer Thickness= 3.402823E+38
Max Layer Thickness= 3.402823E+38
Number of Layers= 5

--- SSHANTYRN.f01 (steady flow) ---

Flow Title=Flow
Program Version=6.20
Number of Profiles= 1
Profile Names=P100yr
River Rch & RM=SSHANTYRN,Main            ,6237
     316
River Rch & RM=SSHANTYRN,Main            ,4998
     356
River Rch & RM=SSHANTYRN,Main            ,3089
     397
Boundary for River Rch & Prof#=SSHANTYRN,Main            , 1
Up Type= 0
Dn Type= 3
Dn Slope=0.036009
DSS Import GetInterval= 0
DSS Import GetPeak= 0
DSS Import FillOption= 0

--- SSHANTYRN.g01 (geometry) ---

Geom Title=Geometry
Program Version=6.20

River Reach=SSHANTYRN       ,Main
Reach XY= 30
     2183557.207      627509.716     2183573.353      627783.153
     2183744.174      628376.904     2183707.599      628483.792
     2183816.061      628665.965     2183950.461      628985.526
     2183964.962      629185.317     2184083.841      629415.623
     2184079.489      629452.217     2183982.988      629483.153
2183958.00737639629536.225040405      2184042.19      629797.129
     2184113.104      629882.964     2184246.451       629854.25
     2184440.689      629927.816     2184431.046       630104.17
     2184543.858      630138.085     2184887.242      630573.537
     2185019.296      630682.793     2185126.565      630855.809
2185328.33993734630946.788591166      2185355.25      631086.135
     2185542.112      631251.022     2185510.592      631382.545
     2185606.184      631545.147      2185934.03      631754.438
      2186041.12      631936.122     2186197.919      632038.726
     2186206.791      632130.133     2186275.121       632242.62

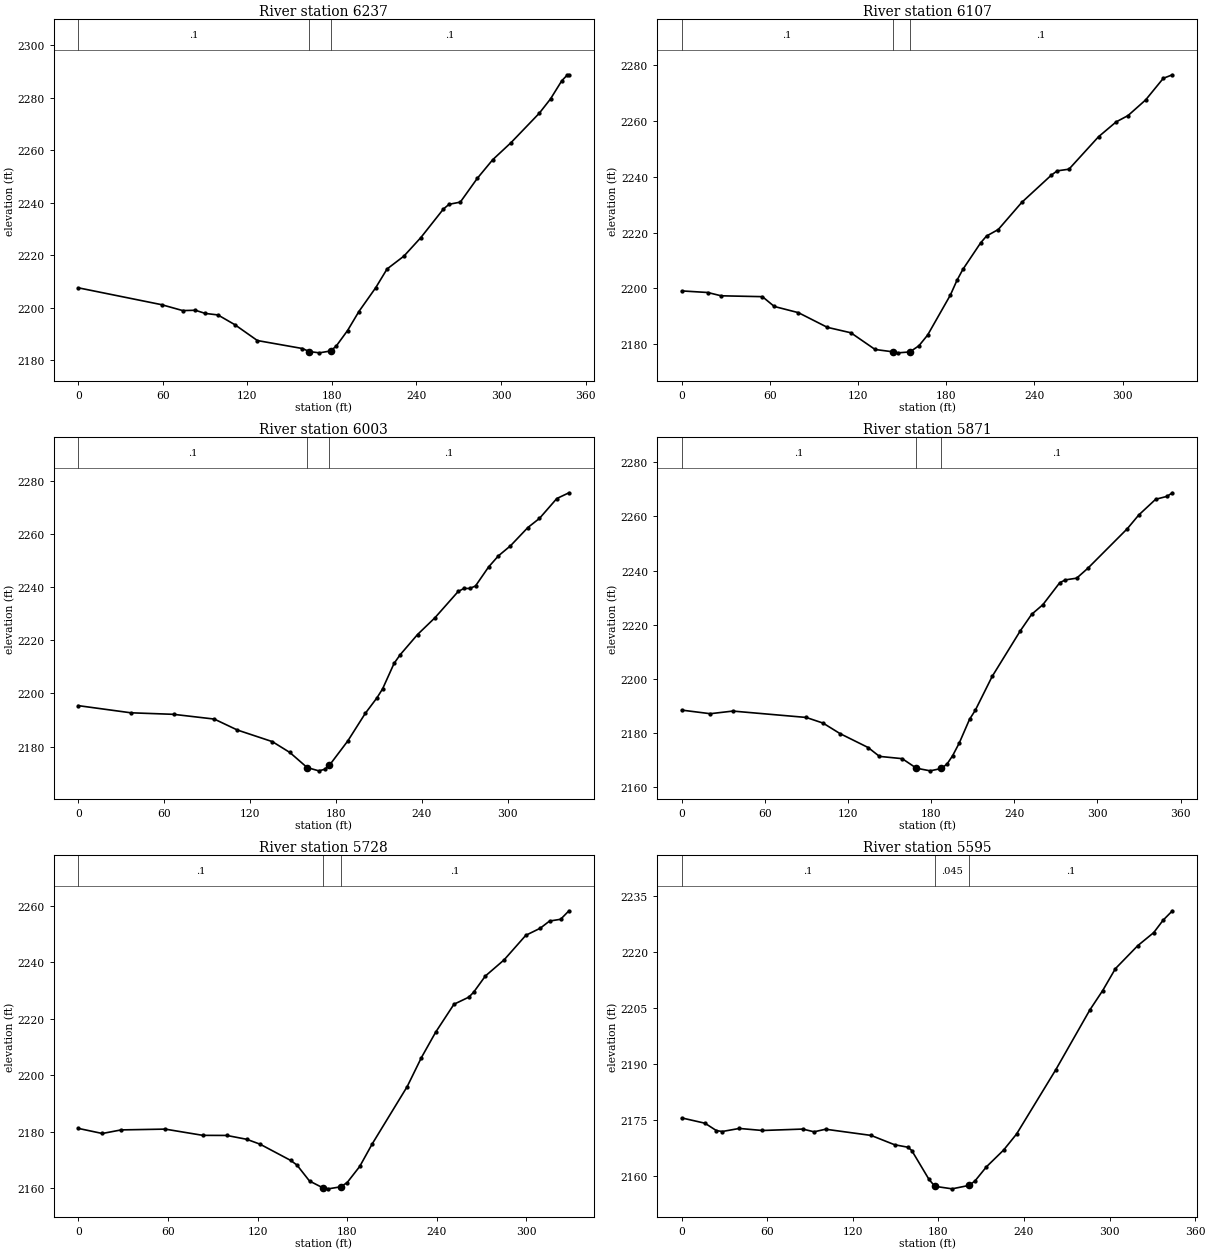
Type RM Length L Ch R = 1 ,6237    ,130.8,130.5,130.1
XS GIS Cut Line= 2
2183385.11148656627526.1191410042183733.35216914627526.119141004
#Sta/Elev= 30
       0 2207.57    59.1 2201.15    74.1  2198.9    83.1 2199.02    90.1 2197.82
    99.1 2197.24   111.1 2193.53   127.1 2187.49   159.1 2184.45     164 2183.29
   171.1 2182.81   179.1 2183.53   183.1 2185.43   191.1 2191.31   199.1 2198.52
   211.1 2207.64   219.1 2214.73   231.1 2219.65   243.1  2226.7   259.1 2237.56
   263.1 2239.36   271.1  2240.2   283.1 2249.22   294.1 2256.35   307.1 2262.85
   327.1 2274.02   335.1 2279.49   343.1 2286.41   347.1 2288.65   348.2 2288.68
#Mann= 3 ,-1,0
       0      .1       0     164    .045       0   179.1      .1       0
Bank Sta=164,179.1
XS Rating Curve= 0 ,0
Exp/Cntr(USF)=0,0
Exp/Cntr=0.3,0.1

Type RM Length L Ch R = 1 ,6107    ,104.4,103.9,103.5
XS GIS Cut Line= 2
2183401.40344832627667.6555587772183734.37041675 627642.19936853
#Sta/Elev= 30
       0 2199.12    17.7 2198.55    26.8 2197.37    54.9 2197.06      63 2193.55
    79.4 2191.33    99.1 2186.08   115.1 2184.13   131.6 2178.15   143.7 2177.32
   147.2 2176.95   155.2 2177.27   161.4 2179.48   167.3 2183.29   182.8 2197.63
   187.3 2202.91   191.3 2206.82   203.4 2216.32   207.4 2218.76   215.4  2221.1
   231.4 2230.82   251.5 2240.56   255.5  2242.1   263.5 2242.69   283.6  2254.3
   295.6 2259.62   303.7 2261.89   315.7  2267.5   327.7 2275.23   333.9 2276.49
#Mann= 3 ,-1,0
       0      .1       0   143.7    .045       0   155.2      .1       0
Bank Sta=143.7,155.2
XS Rating Curve= 0 ,0
Exp/Cntr(USF)=0,0
Exp/Cntr=0.3,0.1

Type RM Length L Ch R = 1 ,6003    ,132,131.9,131.9
XS GIS Cut Line= 2
2183406.49468637627785.7722815232183744.55289285 627728.75041537
#Sta/Elev= 30
       0 2195.42    36.7 2192.73    66.6 2192.15      95 2190.37   111.2 2186.24
   135.6 2181.88   147.8 2177.81   159.9 2172.14     168  2170.9   172.1 2171.47
   175.5 2173.03   188.3 2182.15   200.5 2192.51   208.6 2198.31   212.6 2201.73
   220.6 2211.29   224.8 2214.51     237 2222.16   249.2 2228.49   265.4 2238.35
   269.4 2239.49   273.5 2239.49   277.5 2240.42   286.6 2247.54   293.5 2251.75
   301.9 2255.51   314.1 2262.41   322.2 2265.84   334.3 2273.31   342.8 2275.47
#Mann= 3 ,-1,0
       0      .1       0   159.9    .045       0   175.5      .1       0
Bank Sta=159.9,175.5
XS Rating Curve= 0 ,0
Exp/Cntr(USF)=0,0
Exp/Cntr=0.3,0.1

Type RM Length L Ch R = 1 ,5871    ,143.8,143.2,141.7
XS GIS Cut Line= 2
2183427.87788617627918.1444708082183776.11856875627853.994871386
#Sta/Elev= 30
       0 2188.44    20.6 2187.11    36.9 2188.08    89.8 2185.73     102 2183.64
   114.2 2179.77   134.5 2174.62   142.7 2171.34   159.1  2170.5   169.4 2166.97
   179.3    2166   187.4 2166.88   191.5 2168.55   195.5  2171.6   200.3 2176.31
   207.7 2185.04   211.8 2188.33     224 2200.86   244.3 2217.71   252.5 2223.82
   260.6 2227.38   272.8 2235.52   276.9 2236.56     285 2237.19   293.1 2240.87
   321.6  2255.5   329.8 2260.53     342 2266.34   350.1  2267.4   354.1 2268.74
#Mann= 3 ,-1,0
       0      .1       0   169.4    .045       0   187.4      .1       0
Bank Sta=169.4,187.4
XS Rating Curve= 0 ,0
Exp/Cntr(USF)=0,0
Exp/Cntr=0.3,0.1

Type RM Length L Ch R = 1 ,5728    ,132.5,133.2,136.9
XS GIS Cut Line= 2
2183480.82676189 628074.954602732183793.42877812627974.148089352
#Sta/Elev= 30
       0 2181.11    16.1  2179.3    28.7 2180.57    58.2 2180.85    83.4 2178.64
    99.4 2178.61   112.8 2177.24   121.7 2175.51   142.2 2169.76   146.4 2168.12
   154.8 2162.46   163.7 2160.06   167.4 2159.69   175.7 2160.41     180 2161.91
   188.4 2167.61   196.8 2175.63   220.2 2195.92   229.7 2206.18   239.2 2215.15
   251.5 2225.09   261.5 2227.62   264.7 2229.37   272.5 2235.08   285.1 2240.83
   299.6 2249.52   309.2 2252.01   315.5 2254.57   322.9  2255.2   328.5 2258.21
#Mann= 3 ,-1,0
       0      .1       0   163.7    .045       0   175.7      .1       0
Bank Sta=163.7,175.7
XS Rating Curve= 0 ,0
Exp/Cntr(USF)=0,0
Exp/Cntr=0.3,0.1

Type RM Length L Ch R = 1 ,5595    ,140.3,140.5,137
XS GIS Cut Line= 3
 2183492.0274856628173.7246208892183716.04195977628146.231935422
 2183821.9397112628093.283059708
#Sta/Elev= 30
       0  2175.6    16.3 2174.18    24.3 2172.21    28.4 2171.96    40.4 2172.78
    56.6 2172.23    84.8 2172.61    92.8 2171.88   100.9 2172.57   132.8 2170.91
   149.3 2168.41   158.6 2167.75   161.3 2166.87   173.4 2159.13   177.5 2157.28
   189.6  2156.6   201.6 2157.53   201.6 2157.54   205.7 2158.74   213.7 2162.51
   225.7 2166.98   234.8 2171.28   262.4 2188.57   286.2 2204.53   295.2 2209.72
   304.1 2215.58   319.8 2221.75     331 2225.25   337.6 2228.58   344.1 2231.09
#Mann= 3 ,-1,0
       0      .1       0   177.5    .045       0   201.6      .1       0
Bank Sta=177.5,201.6
XS Rating Curve= 0 ,0
Exp/Cntr(USF)=0,0
Exp/Cntr=0.3,0.1

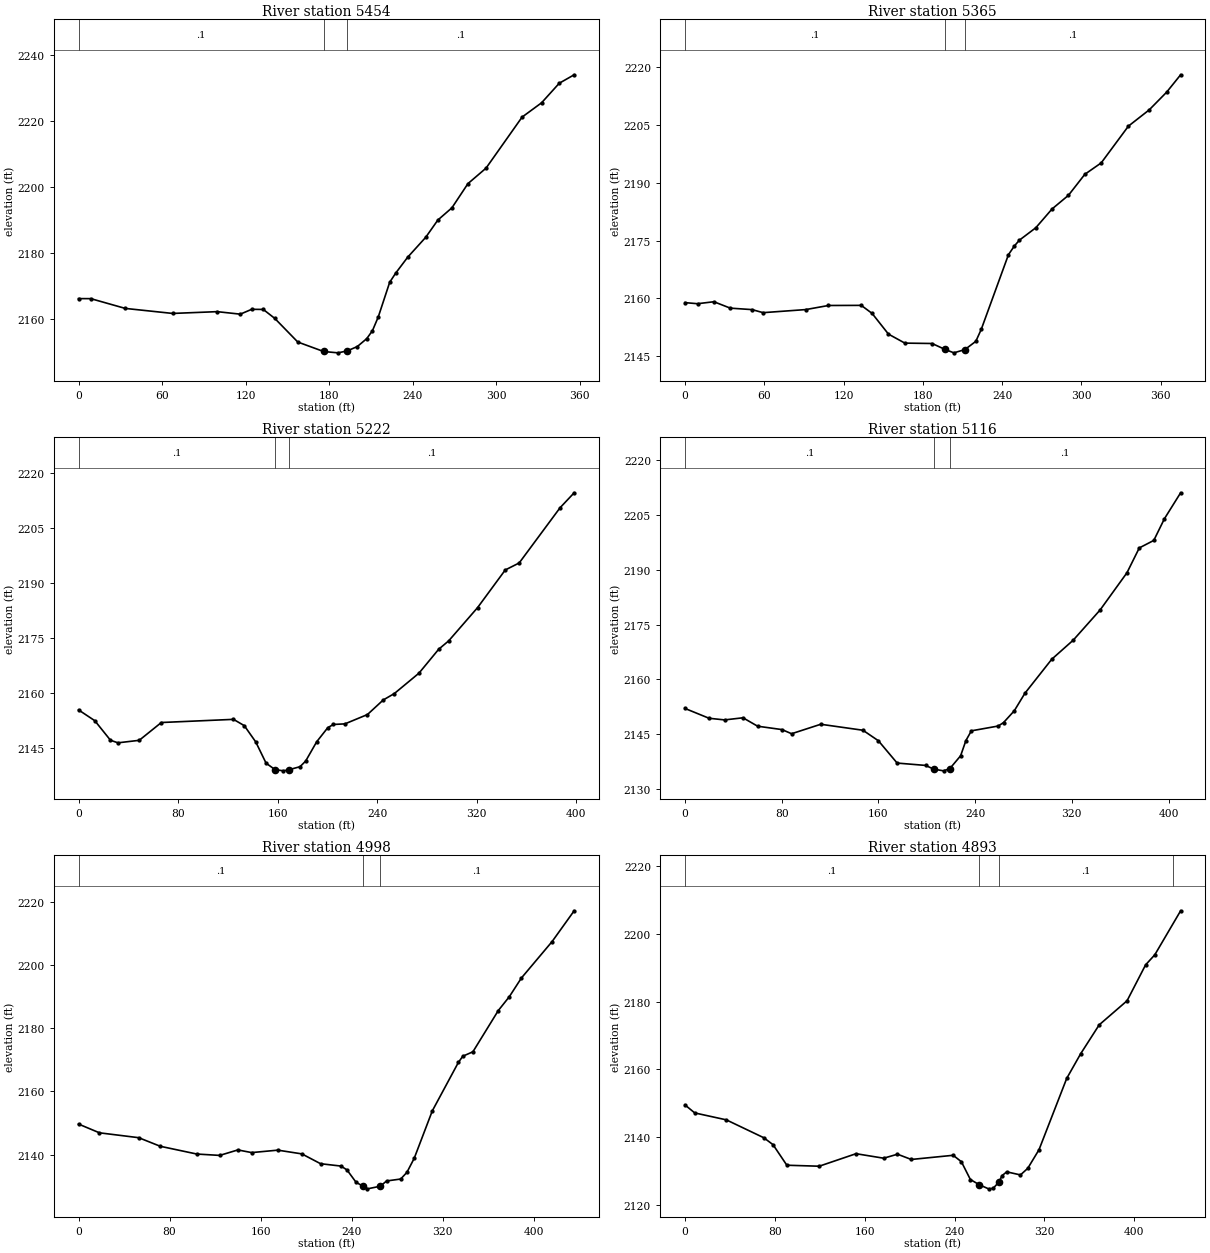
Type RM Length L Ch R = 1 ,5454    ,89.2,89,89
XS GIS Cut Line= 3
2183531.67590472628331.0076257842183749.58089324 628275.00400724
2183870.75235881628225.109874356
#Sta/Elev= 30
       0 2166.14     8.8 2166.13    33.6 2163.17    67.6 2161.65    99.6 2162.19
   116.2 2161.43   124.4  2162.9   132.7 2162.86   140.9 2160.17   157.5 2152.99
     176 2150.13     176 2150.12   186.4 2149.72     1932150.311   200.2 2151.61
     207 2154.01   211.1 2156.41   215.3 2160.59   223.5 2171.08   227.8 2173.85
   236.4 2178.66   249.4 2184.71   258.1 2189.93   268.2 2193.63   279.7 2200.95
   292.7 2205.64   318.6  2221.1   332.6 2225.43   345.3 2231.35     356 2233.91
#Mann= 3 ,-1,0
       0      .1       0     176    .045       0     193      .1       0
Bank Sta=176,193
XS Rating Curve= 0 ,0
Exp/Cntr(USF)=0,0
Exp/Cntr=0.3,0.1

Type RM Length L Ch R = 1 ,5365    ,143.7,143.7,143.8
XS GIS Cut Line= 2
2183542.93986609 628419.122294872183906.45426282628326.461762371
#Sta/Elev= 30
       0 2158.91     9.5 2158.63    21.9 2159.14    34.3 2157.48    50.8  2157.1
    59.1 2156.31    91.4 2157.11   108.6 2158.17   133.4  2158.2   141.6 2156.12
     154 2150.75   166.4 2148.42     187 2148.32   196.7  2146.8   203.5  2145.9
   211.8 2146.74   220.1 2148.88   224.2 2151.97   244.8 2171.34   249.3  2173.6
   253.1  2175.1   265.5 2178.31   277.8 2183.18   290.2 2186.72   302.6 2192.16
     315 2195.12   335.6 2204.65   351.3 2208.85   364.5 2213.44   375.1 2217.95
#Mann= 3 ,-1,0
       0      .1       0   196.7    .045       0   211.8      .1       0
Bank Sta=196.7,211.8
XS Rating Curve= 0 ,0
Exp/Cntr(USF)=0,0
Exp/Cntr=0.3,0.1

Type RM Length L Ch R = 1 ,5222    ,105.2,105.5,105.5
XS GIS Cut Line= 2
2183568.39605634628571.8594363532183925.80096741628395.702599843
#Sta/Elev= 30
       0 2155.47    13.1 2152.52    25.7  2147.2    31.7  2146.5    48.8 2147.18
    66.6 2152.03   124.6 2152.89   133.3 2151.17   142.5 2146.74   150.8 2140.96
     1582139.197   164.8 2138.87   169.5  2139.2   178.1    2140   182.6 2141.52
   191.5 2146.79   200.4 2150.62   204.9  2151.5   214.2 2151.66   232.3  2154.2
     245 2158.17   253.9 2159.91   273.7 2165.46   289.6 2171.99   297.6 2174.26
   320.8  2183.3   343.1 2193.57   354.3 2195.48   387.2 2210.53   398.5 2214.59
#Mann= 3 ,-1,0
       0      .1       0     158    .045       0   169.5      .1       0
Bank Sta=158,169.5
XS Rating Curve= 0 ,0
Exp/Cntr(USF)=0,0
Exp/Cntr=0.3,0.1

Type RM Length L Ch R = 1 ,5116    ,117.9,117.7,117.9
XS GIS Cut Line= 3
 2183564.3230659628628.8813025062183715.02371216628615.644083578
2183948.20241482628503.636846491
#Sta/Elev= 30
       0  2152.1    19.9 2149.42    32.8 2148.97      48 2149.55    60.1 2147.25
    80.2 2146.33    88.2  2145.2   112.3 2147.78   147.2 2146.15     160 2143.28
   175.5 2137.19     199 2136.55   205.8 2135.53   213.9 2135.07   219.1 2135.69
     228 2139.18   232.4 2143.35   236.9 2145.99   259.1  2147.3   263.5 2148.24
   272.4 2151.46   281.2 2156.25   303.4 2165.53   321.2 2170.75   343.4 2178.98
   365.6 2189.13   375.8 2195.91   387.8 2197.96   396.6 2203.88     410 2210.96
#Mann= 3 ,-1,0
       0      .1       0   205.8    .045       0   219.1      .1       0
Bank Sta=205.8,219.1
XS Rating Curve= 0 ,0
Exp/Cntr(USF)=0,0
Exp/Cntr=0.3,0.1

Type RM Length L Ch R = 1 ,4998    ,102.7,105.3,107.6
XS GIS Cut Line= 3
2183576.54203722628730.7060634942183784.26454963628713.395854126
2183987.91407161628612.589340748
#Sta/Elev= 30
       0 2149.66    18.4 2146.89    52.9 2145.35    71.9 2142.63     104 2140.18
   124.1 2139.75   140.1 2141.48   152.2 2140.64   175.2 2141.41   196.3 2140.23
   212.8 2137.12   230.7 2136.38     236 2135.16     244 2131.24   250.3 2129.98
     254 2129.18   265.3 2130.01   270.8 2131.67   283.2 2132.28   288.7  2134.4
   295.1 2138.84     311 2153.83   333.9 2169.13   337.8  2171.1   346.7 2172.51
     369 2185.54   378.7 2189.92   389.3 2195.82   416.3 2207.35   435.7 2217.08
#Mann= 3 ,-1,0
       0      .1       0   250.3    .045       0   265.3      .1       0
Bank Sta=250.3,265.3
XS Rating Curve= 0 ,0
Exp/Cntr(USF)=0,0
Exp/Cntr=0.3,0.1

Type RM Length L Ch R = 1 ,4893    ,131.1,128.2,126.6
XS GIS Cut Line= 4
2183587.74276092628848.8227862412183790.58159359628802.332024347
2183875.82135522628790.241873243 2184018.4614999628754.125758521
#Sta/Elev= 30
       0 2149.52     8.7 2147.16    36.8 2145.12    70.2 2139.84    78.4  2137.8
    90.7 2131.74   119.5 2131.45   152.3 2135.14   176.9 2133.81   189.2 2134.99
   201.5 2133.44   238.8 2134.67   246.1 2132.77   254.1 2127.53   262.2 2125.96
   270.3 2124.78   274.3 2124.91   279.2 2126.65   282.4 2128.71   286.5 2129.79
   298.7 2128.88   305.2 2130.83   315.2 2136.31   339.9 2157.36   352.3 2164.61
   368.8 2173.13   393.6 2180.23   410.1 2190.81   418.3 2193.78   441.3 2206.76
#Mann= 4 ,-1,0
       0      .1       0   262.2    .045       0   279.2      .1       0
  434.19     .08       0
Bank Sta=262.2,279.2
XS Rating Curve= 0 ,0
Exp/Cntr(USF)=0,0
Exp/Cntr=0.3,0.1

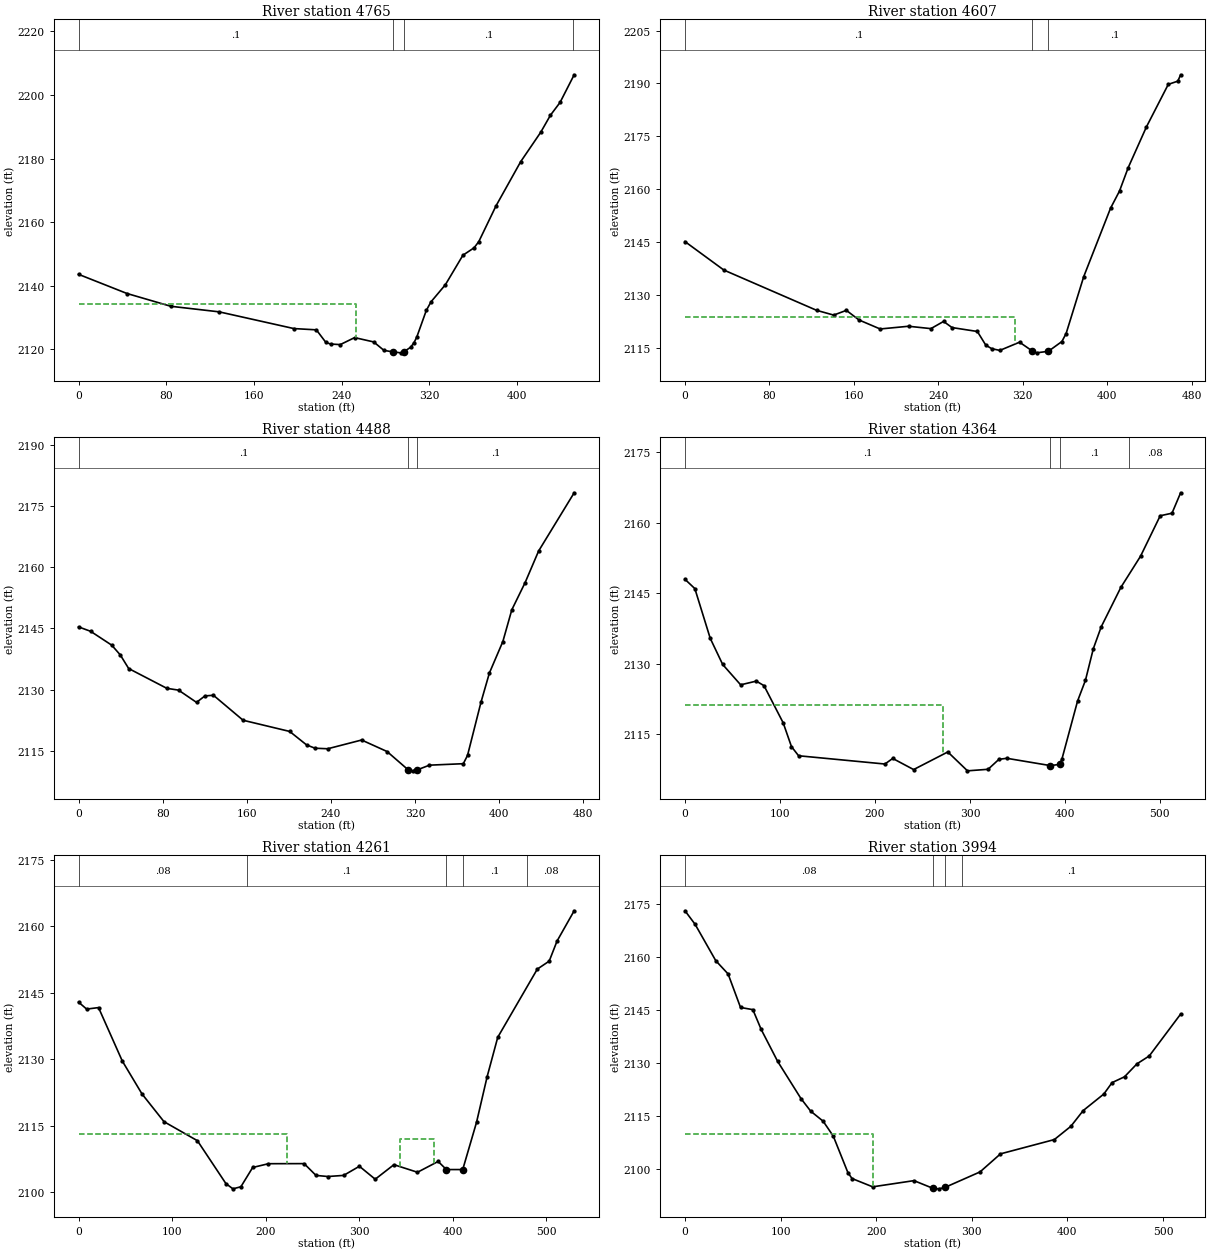
Type RM Length L Ch R = 1 ,4765    ,154.6,157.8,160.4
XS GIS Cut Line= 3
  2183616.253694628960.8300233282183827.03094925628944.538061569
2184047.99068059628848.822786241
#Sta/Elev= 30
       0 2143.61    44.3 2137.57    84.2 2133.56   128.3 2131.81   196.5 2126.55
     217 2126.15   225.7 2122.18     230 2121.69   238.8 2121.51   251.9 2123.71
   269.3 2122.35   278.7 2119.68   286.8 2119.24   293.9 2118.92     297 2119.31
     303 2120.67   306.1 2122.13   308.6 2123.86   317.3 2132.26   321.6 2134.96
   334.7 2140.33   350.7 2149.61   360.9 2151.95   365.2  2153.9   380.9 2165.13
   403.4 2179.02   421.7 2188.28   430.6 2193.66   439.3 2197.64   452.2 2206.35
#Mann= 4 ,-1,0
       0      .1       0   286.8    .045       0     297      .1       0
  451.41     .08       0
#XS Ineff= 2 , 0
          252.71 2134.14
Permanent Ineff=
       F       F
Bank Sta=286.8,297
XS Rating Curve= 0 ,0
Exp/Cntr(USF)=0,0
Exp/Cntr=0.3,0.1

Type RM Length L Ch R = 1 ,4607    ,119.3,119.1,119.3
XS GIS Cut Line= 3
2183627.45441771629067.7460223652183993.00530966629051.454060607
2184090.75708021629016.833641871
#Sta/Elev= 30
       0 2145.15    36.8 2137.08   124.8 2125.64   140.9  2124.3   152.9 2125.64
   164.9 2122.91   184.9 2120.36   211.8 2121.13     233 2120.46     245  2122.5
     253 2120.76     277 2119.65     285 2115.77   290.6 2114.77   298.3 2114.28
     317 2116.61     329 2114.12     329  2114.1   333.1 2113.59   344.3 2114.03
   357.1  2116.8   361.1 2119.07   377.8 2135.22   403.2 2154.62   411.7  2159.5
   419.9 2166.11   437.2 2177.69   457.9 2189.75   466.9 2190.66   469.6 2192.47
#Mann= 3 ,-1,0
       0      .1       0     329    .045       0   344.3      .1       0
#XS Ineff= 2 , 0
             313 2123.62
Permanent Ineff=
       F       F
Bank Sta=329,344.3
XS Rating Curve= 0 ,0
Exp/Cntr(USF)=0,0
Exp/Cntr=0.3,0.1

Type RM Length L Ch R = 1 ,4488    ,125.6,123.8,124.6
XS GIS Cut Line= 3
2183644.76462708629207.2459449192184019.47974751629163.461297694
2184108.06728957629131.895621788
#Sta/Elev= 30
       0 2145.34    11.5 2144.26    31.6 2140.86    39.7 2138.48    47.7 2135.14
      84 2130.29    95.1 2129.85   112.2 2126.85   120.2 2128.43   128.3 2128.59
   156.5 2122.47   200.8 2119.73   216.9 2116.42   224.9 2115.62     237 2115.49
   269.2 2117.63   293.4 2114.81   313.5 2110.32   317.6 2110.08   322.3 2110.34
   333.7 2111.47   365.9 2111.83   369.9 2113.86   382.7 2126.89   390.7 2134.05
   403.5 2141.76     412 2149.52   424.7 2156.21   437.5 2163.93   471.3 2178.19
#Mann= 3 ,-1,0
       0      .1       0   313.5    .045       0   322.3      .1       0
Bank Sta=313.5,322.3
XS Rating Curve= 0 ,0
Exp/Cntr(USF)=0,0
Exp/Cntr=0.3,0.1

Type RM Length L Ch R = 1 ,4364    ,103.2,103.4,103.1
XS GIS Cut Line= 3
2183649.85586513629357.9465911812183776.11856875629339.618134204
2184156.94317485629237.793373215
#Sta/Elev= 30
       0 2147.94    10.4 2145.96    26.6 2135.37    39.7 2129.81    58.6 2125.48
    75.1 2126.27    83.2  2125.3   103.4 2117.38   112.1 2112.33   119.6 2110.38
   210.5 2108.62   218.7 2109.81   240.7 2107.44   276.7 2111.19   297.4 2107.17
   319.1  2107.5   330.5 2109.62   338.8 2109.84   384.8 2108.28   394.3 2108.55
   396.8 2109.65   413.3 2122.03   421.6 2126.45   429.9 2133.18   438.2 2137.83
   458.9 2146.23   479.6 2152.86   500.3 2161.47   512.7 2162.01   521.8 2166.36
#Mann= 4 ,-1,0
       0      .1       0   384.8    .045       0   394.3      .1       0
  467.59     .08       0
#XS Ineff= 2 , 0
          272.13 2121.24
Permanent Ineff=
       F       F
Bank Sta=384.8,394.3
XS Rating Curve= 0 ,0
Exp/Cntr(USF)=0,0
Exp/Cntr=0.3,0.1

Type RM Length L Ch R = 1 ,4261    ,260.6,266.7,266.3
XS GIS Cut Line= 2
2183687.89558448629496.8682496612184189.47681453629325.903218866
#Sta/Elev= 30
       0  2142.9     8.7 2141.32    21.4 2141.66    46.8 2129.61    67.9 2122.17
    91.4 2115.92   127.1 2111.63   157.6 2101.95   165.1 2100.77   173.6 2101.24
   186.2 2105.59   203.1 2106.44   241.2 2106.46   253.9  2103.8   266.5 2103.55
   283.4  2103.8   300.3 2105.86   317.2 2102.94   337.2 2106.22   362.4 2104.51
   384.5 2106.95   393.3 2105.12  410.76 2105.12   425.5 2115.76   436.9 2126.11
   448.2 2134.96   490.5 2150.34   503.2 2152.14   511.6 2156.67   529.9  2163.5
#Mann= 5 ,-1,0
       0     .08       0     180      .1       0   393.3    .045       0
  410.76      .1       0     480     .08       0
#XS Ineff= 2 ,-1
       0  222.582113.132  343.54  379.93 2112.07
Permanent Ineff=
       F       F
Bank Sta=393.3,410.76
XS Rating Curve= 0 ,0
Exp/Cntr(USF)=0,0
Exp/Cntr=0.3,0.1

Type RM Length L Ch R = 1 ,3994    ,135.8,135.5,135.5
XS GIS Cut Line= 2
2183714.37391951629649.4769225032184194.50519779629454.126991962
#Sta/Elev= 30
       0 2173.09    10.6 2169.26    32.2 2158.97    45.1 2155.21    58.1 2145.73
      71 2145.11    79.7 2139.51    96.9 2130.48   121.3 2119.95   131.5 2116.38
   144.5 2113.54   155.1 2109.33   170.4 2098.99   174.7 2097.32   196.3 2094.97
   239.5 2096.72   259.5 2094.53   265.4  2094.4   271.7 2094.78   308.6 2099.19
     330  2104.3   386.3 2108.34   403.6  2112.1   416.5 2116.55   438.1 2121.24
   446.7 2124.46   459.7 2126.11   472.7 2129.77   485.6 2132.01   518.4 2143.85
#Mann= 4 ,-1,0
       0     .08       0   259.5    .045       0   271.7     .08       0
     290      .1       0
#XS Ineff= 2 , 0
          196.72 2109.82
Permanent Ineff=
       F       F
Bank Sta=259.5,271.7
XS Rating Curve= 0 ,0
Exp/Cntr(USF)=0,0
Exp/Cntr=0.3,0.1

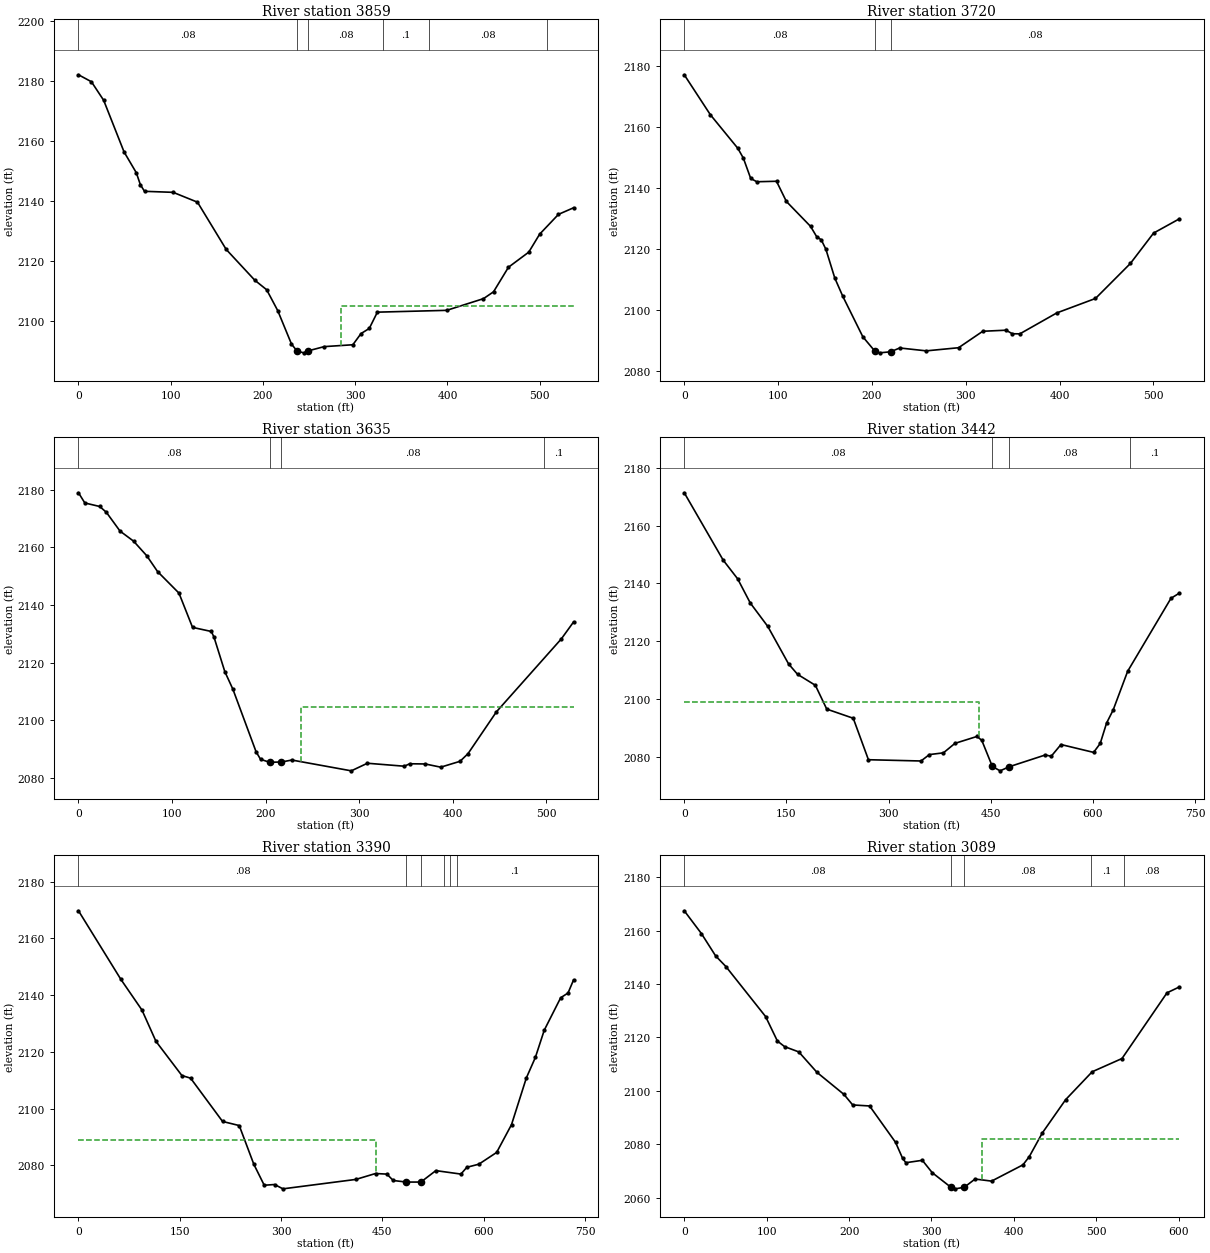
Type RM Length L Ch R = 1 ,3859    ,139.6,138.4,136.8
XS GIS Cut Line= 3
2183763.54550682 629780.392501592184140.45007776629601.207202278
 2184220.9042099629513.210495251
#Sta/Elev= 30
       0 2181.98      14 2179.67    27.3 2173.49    49.4 2156.31    62.7 2149.37
    67.1 2145.39    71.6  2143.2   102.6 2142.86     129 2139.58   160.1 2123.87
   191.1 2113.62     204 2110.44     216 2103.49   230.9 2092.37     237 2090.02
   244.3 2089.45   248.7 2090.09   266.4 2091.52   297.4 2092.14   306.3 2095.87
   315.2 2097.56     324 2102.99   399.1 2103.59     439 2107.48   449.9 2109.76
   466.1 2117.94   488.1 2122.96   499.9 2128.94   520.3 2135.53   536.6 2137.71
#Mann= 6 ,-1,0
       0     .08       0     237    .045       0   248.7     .08       0
     330      .1       0     380     .08       0  507.33      .1       0
#XS Ineff= 2 , 0
                          284.15         2105.01
Permanent Ineff=
       F       F
Bank Sta=237,248.7
XS Rating Curve= 0 ,0
Exp/Cntr(USF)=0,0
Exp/Cntr=0.3,0.1

Type RM Length L Ch R = 1 ,3720    ,85.4,85.4,85.6
XS GIS Cut Line= 3
2183873.55777252629922.4443286472184205.81906012629684.175526046
2184296.32995878629607.492681351
#Sta/Elev= 30
       0 2177.27    27.8 2164.15    57.1  2153.1      63 2149.86    70.8 2143.21
    77.3 2142.12    98.3 2142.28   108.8 2135.65   134.6 2127.45     141 2124.12
     146 2123.02   150.9 2119.96   160.4 2110.48     169 2104.43   190.3 2091.17
   203.4 2086.35   208.1  2085.9   219.8 2086.24   229.6  2087.5   257.9 2086.55
   292.3 2087.58   318.1 2092.99   342.9 2093.34   349.6 2092.17   357.6 2092.14
     397 2099.02   438.2 2103.77   475.4 2115.27   500.1 2125.25   527.5 2129.92
#Mann= 3 ,-1,0
       0     .08       0   203.4    .045       0   219.8     .08       0
Bank Sta=203.4,219.8
XS Rating Curve= 0 ,0
Exp/Cntr(USF)=0,0
Exp/Cntr=0.3,0.1

Type RM Length L Ch R = 1 ,3635    ,200.9,192.8,178.1
BEGIN DESCRIPTION:
Structure XS 4
END DESCRIPTION:
XS GIS Cut Line= 3
2183923.56396232 629986.014631222184168.99419031629818.032919351
2184329.16109434629650.641594453
#Sta/Elev= 30
       0 2178.88     6.8 2175.35    22.7 2174.13    29.8 2172.12    44.4 2165.61
    58.9 2162.12      73 2157.06    84.5  2151.6   107.4 2144.12   121.9 2132.25
     142 2130.83   144.9 2128.82   156.4 2116.93   165.1 2110.78   189.8 2089.18
   194.6 2086.54   204.3 2085.52   216.9 2085.61   228.1 2086.29   291.6 2082.55
   308.8 2085.18   348.3 2084.15     354    2085   370.6 2084.93   387.2 2083.82
   407.8 2085.85   416.3 2088.48   446.7 2102.99   516.1 2128.27   529.1  2134.1
#Mann= 4 ,-1,0
       0     .08       0   204.3    .045       0   216.9     .08       0
  497.41      .1       0
#XS Ineff= 2 , 0
                          238.25          2104.8
Permanent Ineff=
       F       F
Bank Sta=204.3,216.9
XS Rating Curve= 0 ,0
Exp/Cntr(USF)=0,0
Exp/Cntr=0.3,0.1

Type RM Length L Ch R = 1 ,3442    ,52.3,52,51.8
BEGIN DESCRIPTION:
Structure XS 3
END DESCRIPTION:
XS GIS Cut Line= 6
2184087.52663511630155.6323220622184335.74714455630048.301467305
2184300.42900783629911.9396550232184243.49155047 629827.61217933
 2184238.7183115629808.2404346942184343.90725302629647.993631868
#Sta/Elev= 30
       0 2171.38    57.1 2148.07    78.4 2141.58    96.9 2133.22   122.7 2125.08
   153.2  2112.1   166.3 2108.52   192.5 2104.71   209.2 2096.47   248.1  2093.3
   270.4 2078.94   347.6  2078.5   359.9 2080.72   380.5 2081.32   397.4  2084.6
   429.9 2087.01   436.9 2085.61452.31722076.613   463.7 2075.09   477.1 2076.51
     530 2080.58   538.8 2080.15   553.1  2084.2     601 2081.48   610.7 2084.56
   620.1 2091.67   629.7 2096.15     651 2109.57   714.6 2134.84   726.8 2136.61
#Mann= 4 ,-1,0
       0     .08       0452.3172    .045       0   477.1     .08       0
  655.11      .1       0
#XS Ineff= 2 , 0
          432.64  2098.9
Permanent Ineff=
       F       F
Bank Sta=452.3172,477.1
XS Rating Curve= 0 ,0
Exp/Cntr(USF)=0,0
Exp/Cntr=0.3,0.1

Type RM Length L Ch R = 1 ,3390    ,281.1,300.9,316.3
BEGIN DESCRIPTION:
Structure XS 2
END DESCRIPTION:
XS GIS Cut Line= 6
2184097.84451315630163.7958174492184383.36440273 630050.66283689
2184360.04932615629935.6973738592184348.87514113629902.696773005
2184297.47019828629827.8536078952184374.07961791 629661.80518946
#Sta/Elev= 30
       0 2169.69    62.7 2145.54      94  2134.7   114.7 2123.68   153.1 2111.63
     166  2110.7   213.3 2095.45     238    2094   259.6 2080.36     275 2072.97
   290.4 2073.22   302.7  2071.7   410.7 2075.02   439.8  2077.1   456.6 2076.89
     466 2074.64   485.4 2074.09   506.9 2074.09   529.1 2078.12   566.2  2076.9
     575  2079.3   592.7 2080.38   619.1 2084.53   641.1 2094.32   663.1  2110.8
   676.4 2117.99   689.6 2127.62   713.9 2139.04   724.8 2140.72   732.9 2145.28
#Mann= 6 ,-1,0
       0     .08       0   485.4    .045       0   506.9     .08       0
  540.93      .1       0  550.06     .08       0  560.06      .1       0
#XS Ineff= 2 , 0
          441.16 2088.97
Permanent Ineff=
       F       F
Bank Sta=485.4,506.9
XS Rating Curve= 0 ,0
Exp/Cntr(USF)=0,0
Exp/Cntr=0.3,0.1

Type RM Length L Ch R = 1 ,3089    ,76.9,71.4,55.3
BEGIN DESCRIPTION:
Structure XS 1
END DESCRIPTION:
XS GIS Cut Line= 4
2184134.21115779630204.066554947 2184306.3867253 630088.96037837
2184502.49367238630087.7032825552184647.05969107629953.194030386
#Sta/Elev= 30
       0 2167.41    20.8 2158.89    38.1 2150.51    50.5 2146.55    98.7 2127.82
     113 2118.67   121.7 2116.57     139 2114.58   161.1 2106.91   193.8 2098.67
   204.4 2094.73   224.9 2094.35   256.4 2080.73   264.9 2074.79   268.9 2073.11
   288.9 2074.01   300.9 2069.38   323.9 2063.84   328.9 2063.33   339.8 2063.93
   352.9    2067   372.9 2066.22     411 2072.31   418.7  2075.4   434.5 2084.25
   462.8 2096.71     495 2107.15   531.2 2112.11   585.8  2136.7   600.7 2138.89
#Mann= 5 ,-1,0
       0     .08       0   323.9    .045       0   339.8     .08       0
  493.22      .1       0  533.22     .08       0
#XS Ineff= 2 , 0
                          360.84         2081.85
Permanent Ineff=
       F       F
Bank Sta=323.9,339.8
XS Rating Curve= 0 ,0
Exp/Cntr(USF)=0,0
Exp/Cntr=0.3,0.1

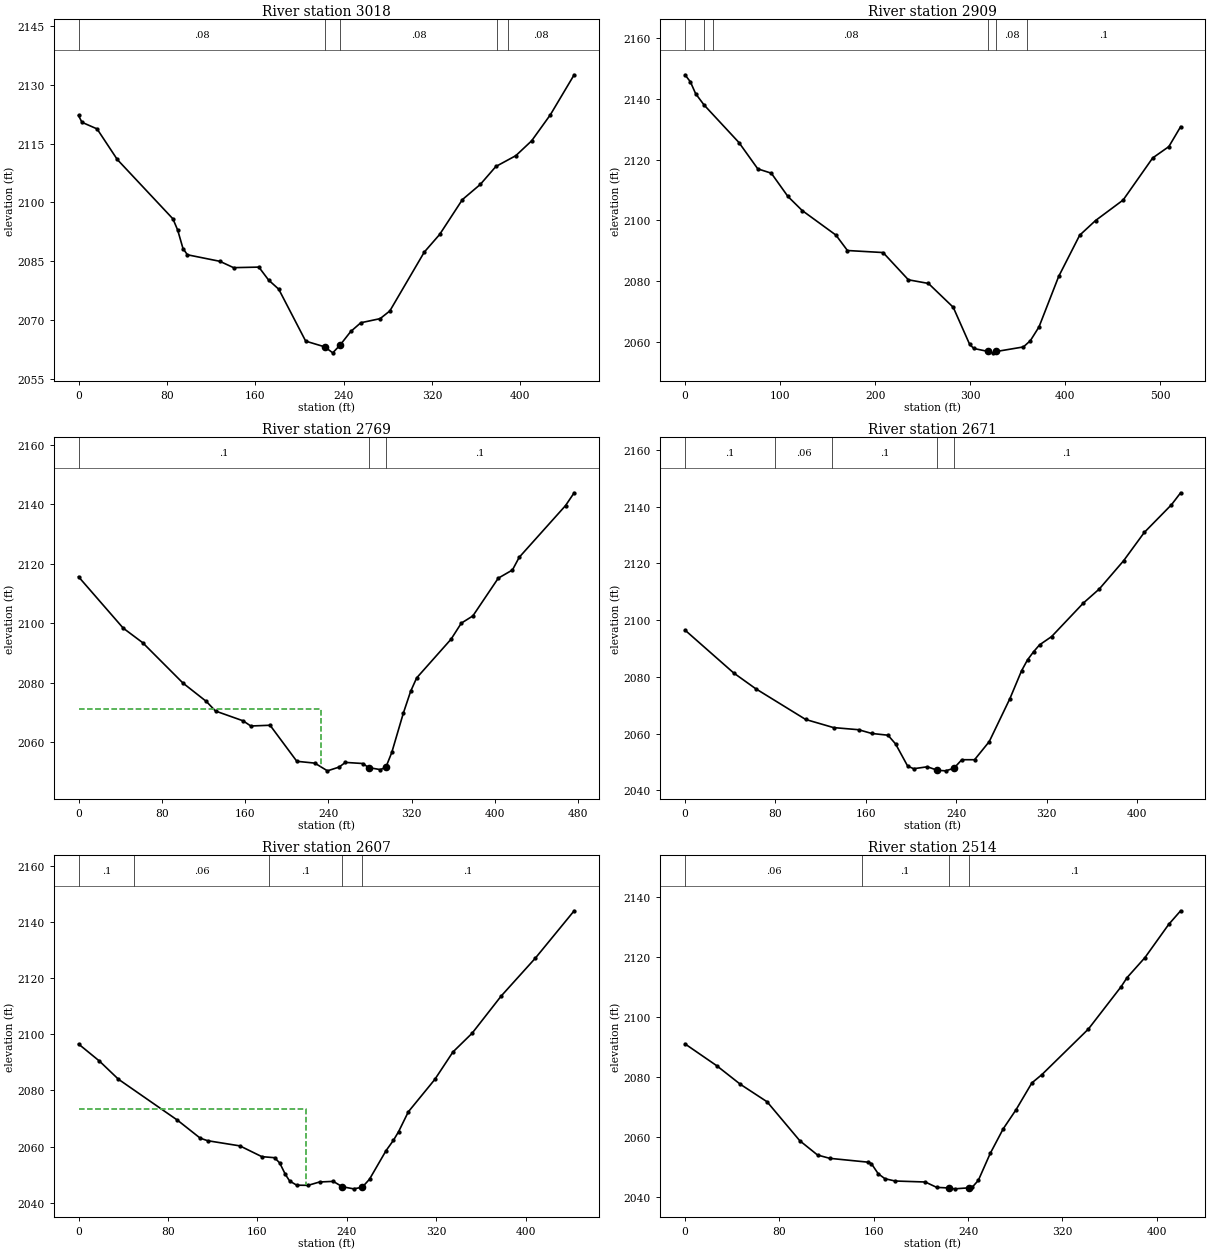
Type RM Length L Ch R = 1 ,3018    ,104.2,108.1,114.4
XS GIS Cut Line= 4
2184317.51012243630260.6369177882184470.09687331630175.643420588
2184484.82015629630102.6962458252184657.48411123630002.310225509
#Sta/Elev= 30
       0 2122.22     3.1 2120.48    16.8 2118.79    35.1 2110.98    85.5 2095.82
    89.8 2092.95    94.6 2088.25    98.6 2086.65     128 2084.98   140.4 2083.36
   163.3  2083.5   172.1  2080.2   181.3 2077.86   205.7  2064.6   222.92063.142
   230.2 2061.61   236.72063.547   246.5 2067.06   255.6 2069.29   273.1 2070.34
   281.9 2072.31   313.1 2087.34     327 2091.84   347.6 2100.74   363.8 2104.61
   377.9 2109.19     396 2111.96   410.3 2115.75   427.2 2122.38   448.8 2132.61
#Mann= 5 ,-1,0
       0     .08       0   222.9    .045       0   236.7     .08       0
  379.08      .1       0  389.08     .08       0
Bank Sta=222.9,236.7
XS Rating Curve= 0 ,0
Exp/Cntr(USF)=0,0
Exp/Cntr=0.3,0.1

Type RM Length L Ch R = 1 ,2909    ,141.6,140.3,138.7
XS GIS Cut Line= 4
2184291.75773905630344.9244255672184411.88022801630238.769667884
2184617.20587774630152.1697339852184713.58322353630052.998841939
#Sta/Elev= 30
       0  2147.9     5.7 2145.58    11.2 2141.69      20    2138    56.8 2125.61
    76.6 2116.96    90.8 2115.54   108.3 2107.88   123.3 2103.26   158.8 2095.18
   170.9 2090.11   208.4 2089.44     235 2080.48   256.1 2079.28   282.2 2071.44
   299.5 2059.22   303.9 2057.89   318.8 2056.92   323.6 2056.46   327.62056.908
     356  2058.4   363.3 2060.45   372.4 2064.98   393.1 2081.58   415.2 2095.14
   431.9 2099.97   460.9 2106.71     492 2120.55     509 2124.28   521.4 2130.83
#Mann= 6 ,-1,0
       0     .08       0      20      .1       0      30     .08       0
   318.8    .045       0   327.6     .08       0  360.31      .1       0
Bank Sta=318.8,327.6
XS Rating Curve= 0 ,0
Exp/Cntr(USF)=0,0
Exp/Cntr=0.3,0.1

Type RM Length L Ch R = 1 ,2769    ,98,98.6,99.9
XS GIS Cut Line= 2
2184466.35437998630473.4275532892184797.38961117630131.218137074
#Sta/Elev= 30
       0 2115.63    42.9 2098.39    61.6  2093.5   100.4 2079.92   122.8 2073.77
   131.6 2070.55     158 2067.28   165.5 2065.53     184 2065.78   209.7 2053.68
     227 2053.07   239.1 2050.48   250.4 2051.75   256.3 2053.31     273 2052.94
   278.7 2051.57     290 2050.89   295.3 2051.74   300.9 2056.64     312 2069.83
     319 2077.14   324.8 2081.67   357.9 2094.69   367.7 2100.05   378.8 2102.48
   403.2 2115.15   416.8 2117.89   423.3 2122.15   467.8 2139.51   476.1 2143.81
#Mann= 3 ,-1,0
       0      .1       0   278.7    .045       0   295.3      .1       0
#XS Ineff= 2 , 0
          233.15 2071.35
Permanent Ineff=
       F       F
Bank Sta=278.7,295.3
XS Rating Curve= 0 ,0
Exp/Cntr(USF)=0,0
Exp/Cntr=0.3,0.1

Type RM Length L Ch R = 1 ,2671    ,63,63.7,64.3
XS GIS Cut Line= 2
2184535.68240658630506.2480474952184866.28703349 630217.80554912
#Sta/Elev= 30
       0 2096.51    43.1 2081.39    62.5 2075.86   106.8 2064.99   131.5 2062.12
   153.7 2061.37   165.2 2060.06   179.7 2059.43   186.4 2056.36   197.1 2048.54
   202.4 2047.62   214.6  2048.3   223.42047.063   230.7 2046.87     2382047.772
     245 2050.79   256.3 2050.79   269.3 2057.18   287.6 2072.35   297.9 2082.15
   303.2 2086.02   308.5 2088.84   313.8 2091.29   324.5 2094.22   352.6 2106.04
   366.7    2111   388.2 2120.95   406.5 2130.93   430.6 2140.72   438.7 2144.93
#Mann= 5 ,-1,0
       0      .1       0      80     .06       0     130      .1       0
   223.4    .045       0     238      .1       0
Bank Sta=223.4,238
XS Rating Curve= 0 ,0
Exp/Cntr(USF)=0,0
Exp/Cntr=0.3,0.1

Type RM Length L Ch R = 1 ,2607    ,92.2,92.4,92.3
XS GIS Cut Line= 2
2184562.52603118630549.5941816332184911.43995841630276.385357911
#Sta/Elev= 30
       0 2096.53    18.6 2090.48    35.7 2083.97    88.5 2069.38   108.8 2062.99
   115.4 2062.08   144.3 2060.23   163.9  2056.4   175.3 2056.02   179.9 2054.15
     185 2050.04   188.8 2047.72   195.1 2046.23   205.3 2046.18   215.5 2047.37
   227.8 2047.59   235.8 2045.68     246 2044.93   253.7  2045.5   260.2 2048.36
     275 2058.54   281.5 2062.16   286.2 2065.29   294.9 2072.36   318.6 2083.91
   334.8 2093.68   351.9 2100.34     378 2113.64   408.5 2127.11   443.2 2143.98
#Mann= 5 ,-1,0
       0      .1       0      50     .06       0     170      .1       0
   235.8    .045       0   253.7      .1       0
#XS Ineff= 2 , 0
           203.1 2073.25
Permanent Ineff=
       F       F
Bank Sta=235.8,253.7
XS Rating Curve= 0 ,0
Exp/Cntr(USF)=0,0
Exp/Cntr=0.3,0.1

Type RM Length L Ch R = 1 ,2514    ,62.8,63.8,62.6
XS GIS Cut Line= 2
2184626.90606097630613.521954209 2184960.1741967 630357.53338619
#Sta/Elev= 30
       0 2090.94    26.8 2083.69      47 2077.45    69.6 2071.64    97.4 2058.63
   112.4 2053.89   122.7 2052.79   155.2 2051.51     158 2051.04   163.8 2047.66
   169.5    2046   178.1 2045.23   203.7  2044.9   213.4 2043.11   223.5 2042.91
   228.6 2042.62   240.8 2042.96   243.7 2043.24   248.7 2045.45   258.8 2054.44
   269.8 2062.63   280.7 2069.01   294.1 2077.93   302.6  2080.7     342 2095.88
   369.8 2110.03   374.8 2113.03     390 2119.72   410.1 2130.77   420.2  2135.3
#Mann= 4 ,-1,0
       0     .06       0     150      .1       0   223.5    .045       0
   240.8      .1       0
Bank Sta=223.5,240.8
XS Rating Curve= 0 ,0
Exp/Cntr(USF)=0,0
Exp/Cntr=0.3,0.1