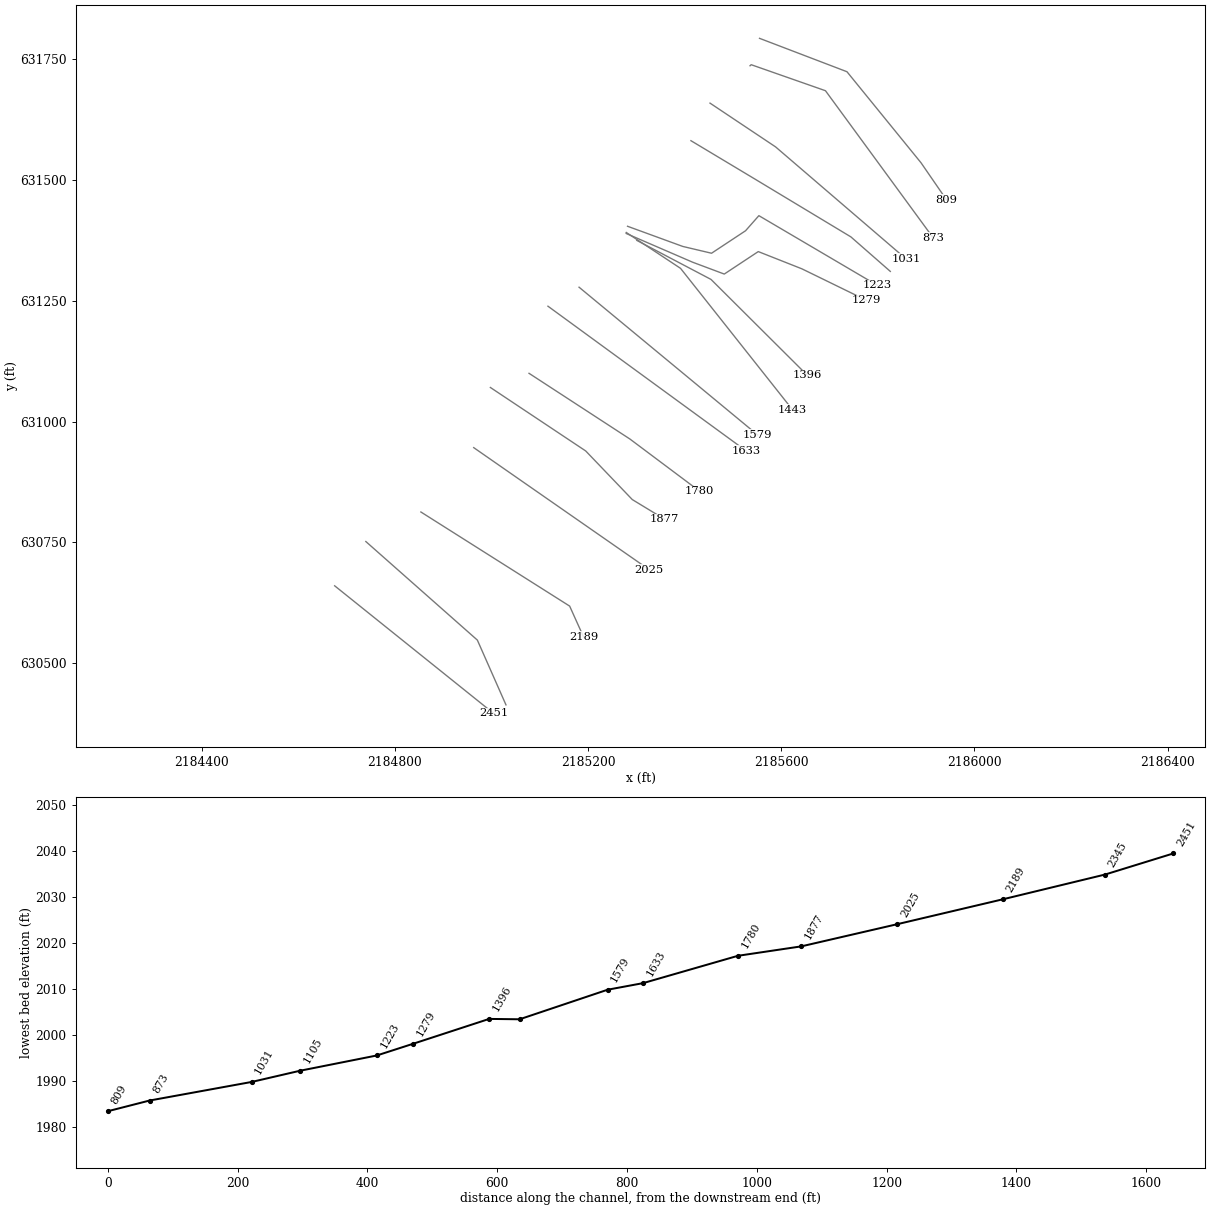
HEC-RAS study SSHANTYRN.prj: SSHANTYRN

--- SSHANTYRN.g01 (geometry) --- (continued)

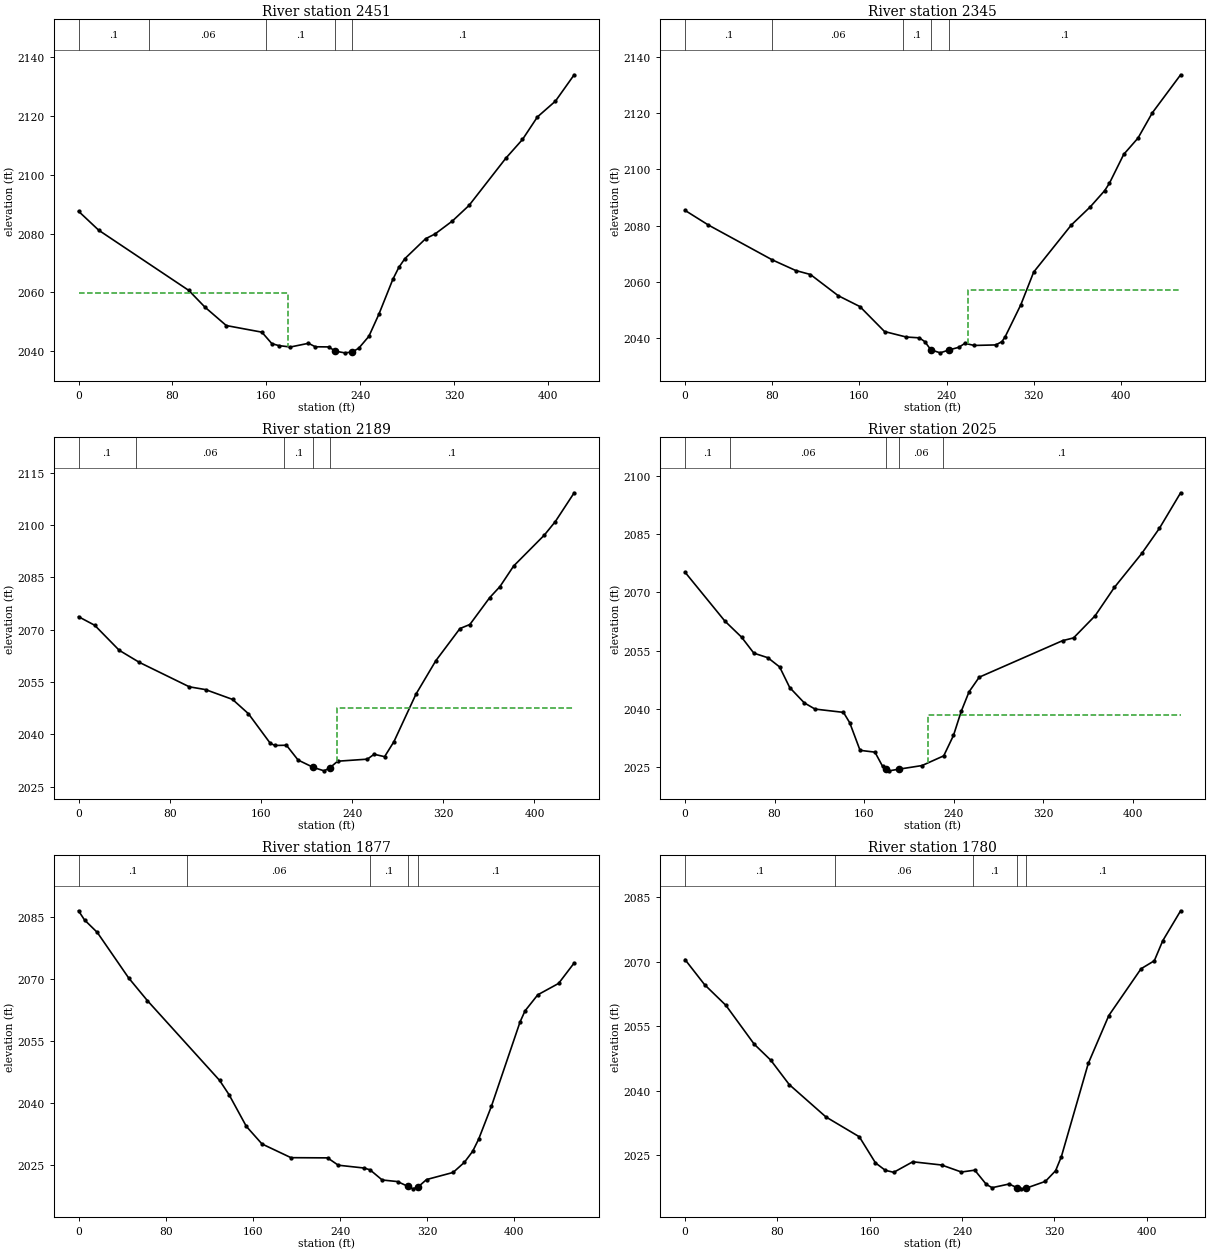
Type RM Length L Ch R = 1 ,2451    ,105.4,105.3,103.7
XS GIS Cut Line= 2
2184675.49132876630659.9249485012185004.57107758630395.795150108
#Sta/Elev= 30
       0 2087.58    17.2 2081.13    93.9 2060.68   107.7 2054.99   125.8 2048.76
   156.1 2046.51   164.6 2042.62   170.5 2041.95   180.4 2041.47   195.8 2042.73
   201.6 2041.55     213  2041.5   218.7 2040.06   226.6 2039.49   232.9 2039.74
   238.6 2041.06   247.2 2045.09   255.7 2052.57   267.6 2064.43   272.7 2068.49
   277.8 2071.45   295.5 2078.24   303.5 2079.84   318.3 2084.25   332.5 2089.55
   363.8 2105.57     378 2111.94   390.7 2119.59   406.1 2124.98     422 2133.91
#Mann= 5 ,-1,0
       0      .1       0      60     .06       0     160      .1       0
   218.7    .045       0   232.9      .1       0
#XS Ineff= 2 , 0
          178.51 2059.89
Permanent Ineff=
       F       F
Bank Sta=218.7,232.9
XS Rating Curve= 0 ,0
Exp/Cntr(USF)=0,0
Exp/Cntr=0.3,0.1

Type RM Length L Ch R = 1 ,2345    ,156.5,156.8,158.4
XS GIS Cut Line= 3
2184740.05589567630751.5675758562184970.94249363630547.499021942
2185030.16567424 630413.40880171
#Sta/Elev= 30
       0 2085.44    21.5 2080.23    80.2 2067.85   101.6  2064.1   115.1 2062.68
   140.6 2055.16   160.5  2051.3   183.1 2042.44     203  2040.5     215 2040.21
     220 2038.86   225.6 2035.96   234.1 2034.89   242.6 2035.96   251.2 2036.85
   256.8 2038.27   265.3 2037.51   285.2  2037.7   290.8 2038.89   293.8 2040.65
   308.1 2051.95   319.9 2063.55   354.4 2080.24   371.9 2086.72     385 2092.43
   389.4 2095.08   402.5 2105.31   415.6 2111.09   428.7 2120.03   454.7 2133.54
#Mann= 5 ,-1,0
       0      .1       0      80     .06       0     200      .1       0
   225.6    .045       0   242.6      .1       0
#XS Ineff= 2 , 0
                          259.56         2057.04
Permanent Ineff=
       F       F
Bank Sta=225.6,242.6
XS Rating Curve= 0 ,0
Exp/Cntr(USF)=0,0
Exp/Cntr=0.3,0.1

Type RM Length L Ch R = 1 ,2189    ,163.5,163.2,163.1
XS GIS Cut Line= 3
2184854.03258287630812.7462388372185162.02105746630617.896387563
 2185190.9342612630553.784501015
#Sta/Elev= 30
       0 2073.71    14.2 2071.25    35.7 2064.08    53.4 2060.61    97.2 2053.61
   111.4 2052.81   135.1    2050   149.1 2045.88   168.2 2037.42   172.3 2036.79
   182.4 2036.86   192.6 2032.62   206.1 2030.48   215.5 2029.52   220.62030.419
   227.3 2032.28   253.4 2032.87   259.3 2034.27   268.5 2033.58   276.7 2037.89
     296 2051.49   313.4 2061.07   334.6 2070.31   343.3 2071.47   360.7 2079.17
   369.7 2082.34   381.7 2088.24   408.6 2097.09   418.3 2100.99   434.8 2109.23
#Mann= 5 ,-1,0
       0      .1       0      50     .06       0     180      .1       0
   206.1    .045       0   220.6      .1       0
#XS Ineff= 2 , 0
                          226.78         2047.44
Permanent Ineff=
       F       F
Bank Sta=206.1,220.6
XS Rating Curve= 0 ,0
Exp/Cntr(USF)=0,0
Exp/Cntr=0.3,0.1

Type RM Length L Ch R = 1 ,2025    ,150.9,148.1,147.4
XS GIS Cut Line= 2
2184963.39991875630945.9983951922185326.70060919630693.322136443
#Sta/Elev= 30
       0 2075.23    35.6 2062.64    50.5  2058.5    61.5 2054.37      74  2053.2
    84.5 2050.83    93.5 2045.52   106.5 2041.58   116.1 2039.98   141.5 2039.13
   147.1 2036.45   156.3 2029.36   169.6 2028.89   176.4 2025.25   179.3 2024.48
   182.2 2024.08     191 2024.51   211.6 2025.44     231 2027.94   239.7 2033.19
   246.6 2039.38   253.6 2044.42   262.7 2048.19   337.1 2057.59   346.9  2058.3
   366.1 2063.98   383.3 2071.28   407.8 2080.04   423.6 2086.53   442.5 2095.66
#Mann= 5 ,-1,0
       0      .1       0      40     .06       0   179.3    .045       0
     191     .06       0     230      .1       0
#XS Ineff= 2 , 0
                          216.76         2038.58
Permanent Ineff=
       F       F
Bank Sta=179.3,191
XS Rating Curve= 0 ,0
Exp/Cntr(USF)=0,0
Exp/Cntr=0.3,0.1

Type RM Length L Ch R = 1 ,1877    ,96.8,97.5,96.9
XS GIS Cut Line= 4
2184997.89541806631070.5305911442185195.34997274630939.028692851
2185291.72055225630838.4419004952185358.68191687630797.740799361
#Sta/Elev= 30
       0 2086.41     5.5  2084.2    17.2 2081.19      46 2070.19    63.2 2064.71
   129.5 2045.43   138.2 2041.97     154 2034.34   168.4 2030.08     195 2026.77
   228.6 2026.72   238.4 2024.95     262 2024.27   267.5 2023.84   278.7 2021.38
   292.9 2020.99     302 2019.87     307 2019.24   311.8 2019.73   319.4 2021.48
   343.8  2023.2   354.1 2025.63   361.7 2028.29   367.2 2031.21     379 2039.22
   405.2 2059.53   409.8 2062.23   421.5 2066.11   440.6 2068.86   454.9  2073.8
#Mann= 5 ,-1,0
       0      .1       0     100     .06       0  267.24      .1       0
     302    .045       0   311.8      .1       0
Bank Sta=302,311.8
XS Rating Curve= 0 ,0
Exp/Cntr(USF)=0,0
Exp/Cntr=0.3,0.1

Type RM Length L Ch R = 1 ,1780    ,147,146.3,145.5
XS GIS Cut Line= 3
2185077.89832898631099.8470973972185286.90202327630963.723653849
 2185430.8555764 630855.90906803
#Sta/Elev= 30
       0  2070.5      17 2064.65    35.4 2059.86      60 2050.81    74.3  2047.1
    90.3 2041.43   122.1  2033.9     151 2029.29     165 2023.22   173.5  2021.5
   180.8 2021.03   197.3 2023.48   222.3 2022.73   239.4  2021.1     251 2021.53
     261 2018.22     266 2017.46   280.7 2018.31   287.72017.438     291 2017.19
     295  2017.3   312.2 2018.93     321  2021.4     326 2024.67   349.3 2046.34
   367.1 2057.48     395 2068.35   406.5 2070.21   413.8 2074.86   429.3 2081.83
#Mann= 5 ,-1,0
       0      .1       0     130     .06       0  249.42      .1       0
   287.7    .045       0     295      .1       0
Bank Sta=287.7,295
XS Rating Curve= 0 ,0
Exp/Cntr(USF)=0,0
Exp/Cntr=0.3,0.1

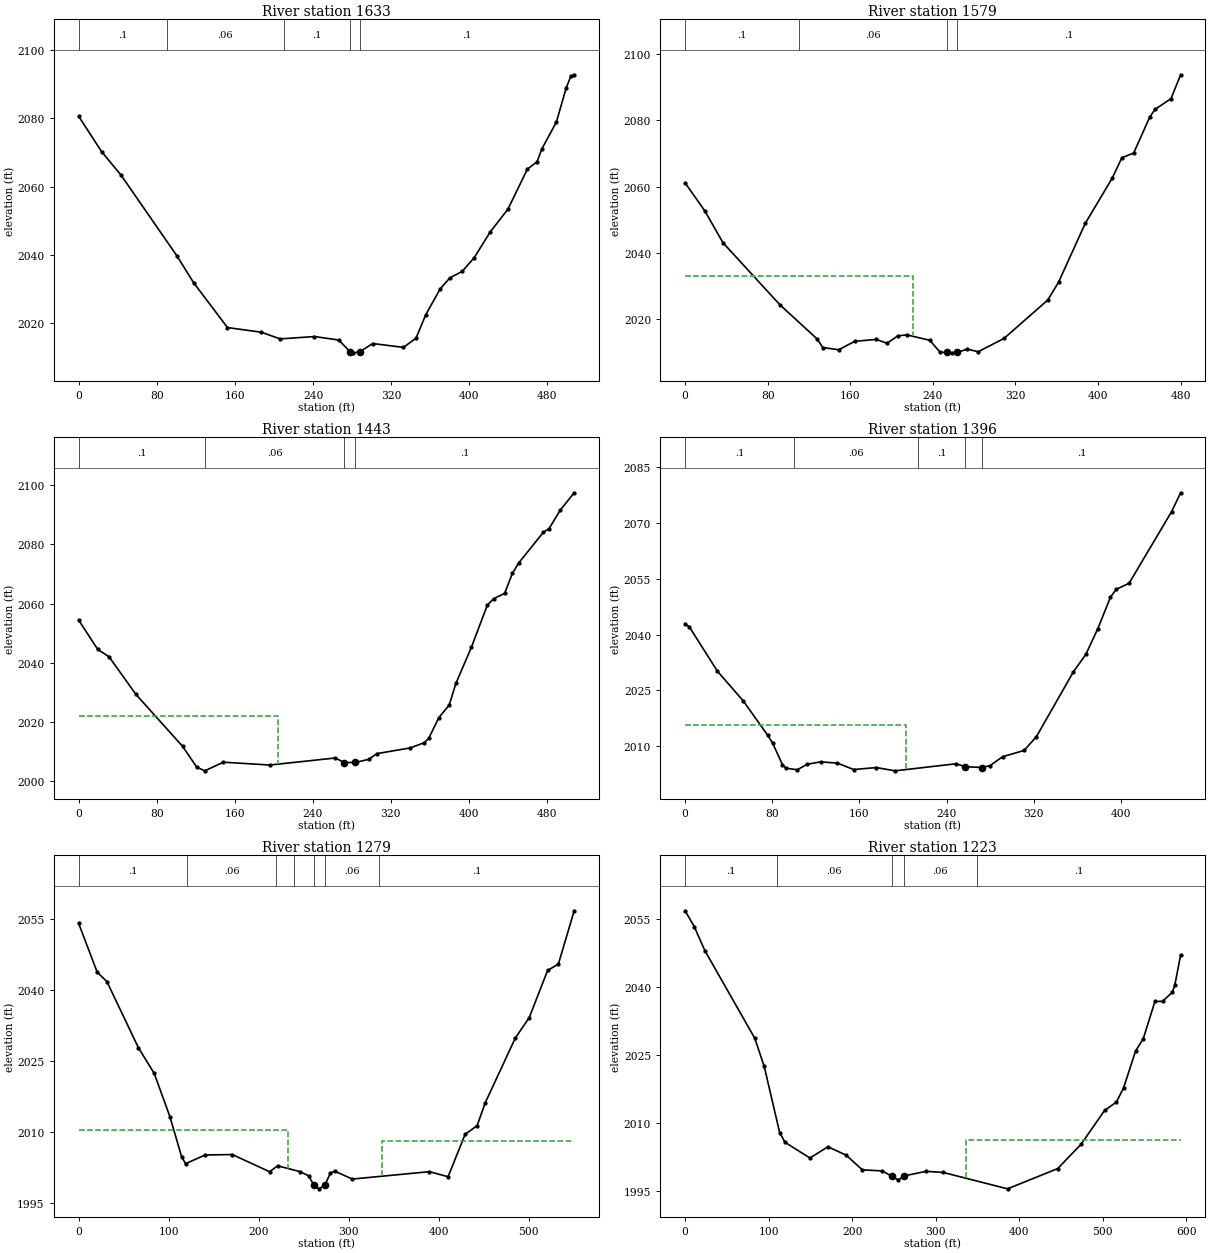
Type RM Length L Ch R = 1 ,1633    ,54.8,54.5,54.2
XS GIS Cut Line= 2
2185117.09136137631238.8016143882185526.90459695630939.612810497
#Sta/Elev= 30
       0 2080.64    23.6 2070.23    43.4 2063.37   100.7 2039.66   117.7 2031.82
   152.4 2018.65   187.1 2017.28   206.3 2015.32   241.5 2016.01   266.3 2014.99
   278.2  2011.5     281 2011.23   287.7  2011.5   301.1 2013.96   332.6 2012.83
   345.5 2015.54   355.4  2022.4   370.3 2030.03   380.2 2033.24   392.7 2035.11
     405 2039.13   421.3 2046.64   439.6  2053.4   459.5 2065.13   469.4 2067.29
   474.3 2071.06   489.2 2078.94   499.1 2088.84     504 2092.39   507.4 2092.81
#Mann= 5 ,-1,0
       0      .1       0      90     .06       0     210      .1       0
   278.2    .045       0   287.7      .1       0
Bank Sta=278.2,287.7
XS Rating Curve= 0 ,0
Exp/Cntr(USF)=0,0
Exp/Cntr=0.3,0.1

Type RM Length L Ch R = 1 ,1579    ,136.7,135.6,134.5
XS GIS Cut Line= 2
2185181.49670194631278.1326694772185551.31880078630972.156079555
#Sta/Elev= 30
       0 2061.15    19.1 2052.68    36.7 2043.06    91.7 2024.36   128.1 2013.93
   133.3 2011.41   148.8 2010.73   164.4 2013.28   185.2 2013.86   195.6 2012.67
   205.9 2014.92   214.8 2015.23   237.1 2013.58   246.9    2010   253.92009.904
   258.8  2009.8   263.32009.903   273.4 2010.93   283.9 2010.13     309 2014.17
   351.3 2025.76   361.7 2031.12   387.7 2048.96   413.6  2062.5   423.1 2068.75
   434.5 2070.15     450 2080.98   455.1 2083.32   470.7 2086.61     480  2093.8
#Mann= 4 ,-1,0
       0      .1       0     110     .06       0   253.9    .045       0
   263.3      .1       0
#XS Ineff= 2 , 0
           220.4 2032.98
Permanent Ineff=
       F       F
Bank Sta=253.9,263.3
XS Rating Curve= 0 ,0
Exp/Cntr(USF)=0,0
Exp/Cntr=0.3,0.1

Type RM Length L Ch R = 1 ,1443    ,45.2,46.9,47.3
BEGIN DESCRIPTION:
Structure XS 4
END DESCRIPTION:
XS GIS Cut Line= 3
2185279.23881982631391.4549937122185391.61142813 631317.15461962
2185623.51612659631024.390208108
#Sta/Elev= 30
       0  2054.4    19.6 2044.48    31.2 2041.97    58.7 2029.27   106.6 2011.66
     121 2004.66   129.3 2003.36   148.5 2006.29   195.9 2005.33   263.2 2007.71
   272.5 2006.17   283.8 2006.19   297.4 2007.25   305.9 2009.19   340.1 2011.12
   354.7 2012.92   359.2 2014.48   369.4 2021.36     380 2025.62   386.9 2032.95
   402.8  2045.2   419.1 2059.43   425.5 2061.62   436.9 2063.43   444.8 2070.18
   451.3 2073.73   476.6 2084.13   482.5  2085.4   493.9 2091.62   508.2  2097.5
#Mann= 4 ,-1,0
       0      .1       0     130     .06       0   272.5    .045       0
   283.8      .1       0
#XS Ineff= 2 , 0
          204.37  2021.9
Permanent Ineff=
       F       F
Bank Sta=272.5,283.8
XS Rating Curve= 0 ,0
Exp/Cntr(USF)=0,0
Exp/Cntr=0.3,0.1

Type RM Length L Ch R = 1 ,1396    ,105.7,117.3,124.6
XS GIS Cut Line= 3
2185301.03969164 631375.021661292185454.72065014631294.229385964
2185654.06680773631095.761405272
#Sta/Elev= 30
       0 2042.86       4 2042.02    29.7 2030.16    53.3 2022.23    75.8    2013
    80.4 2010.86    89.4 2005.07    92.5 2004.17     103 2003.72     112  2005.2
   124.3 2005.85   139.9 2005.51   154.7 2003.79   175.7 2004.32   192.6 2003.44
   248.8 2005.34   257.4 2004.55   272.62004.334     280 2004.85   291.4 2007.22
   311.2 2008.91   322.5  2012.6   356.4 2029.98   367.9  2034.7   378.9 2041.59
   390.5 2050.05   395.8 2052.12   407.6 2053.77   446.6 2072.98   454.9 2078.04
#Mann= 5 ,-1,0
       0      .1       0     100     .06       0  213.62      .1       0
   257.4    .045       0   272.6      .1       0
#XS Ineff= 2 , 0
           203.1 2015.83
Permanent Ineff=
       F       F
Bank Sta=257.4,272.6
XS Rating Curve= 0 ,0
Exp/Cntr(USF)=0,0
Exp/Cntr=0.3,0.1

Type RM Length L Ch R = 1 ,1279    ,56.8,55.7,58.4
BEGIN DESCRIPTION:
Structure XS 3
END DESCRIPTION:
XS GIS Cut Line= 6
2185279.11397436631389.3441649422185416.41862018631329.972476433
2185482.13071816631305.3526922132185552.52808378631351.865237356
2185642.96622969631316.1326960282185777.04512066631250.664794006
#Sta/Elev= 30
       0 2054.15    20.6 2043.84    31.4 2041.84    66.5 2027.83      84 2022.42
   101.4 2013.29   114.5 2004.77   118.8 2003.34   140.6 2005.18   170.7 2005.27
   212.2 2001.64   221.1 2002.89   246.2 2001.65   255.8 2000.75261.19221998.823
   267.3 1998.02273.53221998.805   279.7 2001.34   284.5 2001.77   304.1 2000.09
   389.8 2001.65   410.5 2000.58   429.4 2009.53   442.8 2011.39   451.7 2016.18
   485.2  2029.9   500.7 2034.24   521.1 2044.19   533.1 2045.56   550.6 2056.81
#Mann= 7 ,-1,0
       0      .1       0     120     .06       0  219.59      .1       0
  239.76     .06       0261.1922    .045       0273.5322     .06       0
  334.14      .1       0
#XS Ineff= 2 , 0
          232.79  2010.5  336.75          2008.1
Permanent Ineff=
       F       F
Bank Sta=261.1922,273.5322
XS Rating Curve= 0 ,0
Exp/Cntr(USF)=0,0
Exp/Cntr=0.3,0.1

Type RM Length L Ch R = 1 ,1223    ,120.9,118.4,107.7
BEGIN DESCRIPTION:
Structure XS 2
END DESCRIPTION:
XS GIS Cut Line= 6
2185281.87930325631404.2913797022185396.20095789631362.540790191
2185455.76581753 631348.459128842185526.16318315631394.971673983
2185553.79404538631426.259069724 2185798.7163183631282.161839028
#Sta/Elev= 30
       0 2056.92      11 2053.42    23.7  2048.1    83.4 2028.75    94.7 2022.53
   113.2 2007.91   119.6 2005.76   149.4 2002.29     171 2004.78     193  2002.9
   212.2 1999.67   236.1 1999.44247.28891998.274   255.3 1997.42261.68891998.318
   288.5 1999.35     309  1999.1     386 1995.48     446 1999.95   474.2 2005.37
   502.1 2012.79   516.3 2014.65   524.9 2017.79   539.2 2025.89   548.5 2028.67
   562.4 2036.88   571.5 2036.92   583.3 2038.92   586.2 2040.48   593.2 2047.14
#Mann= 5 ,-1,0
       0      .1       0     110     .06       0247.2889    .045       0
261.6889     .06       0  349.03      .1       0
#XS Ineff= 2 , 0
                          336.17         2006.17
Permanent Ineff=
       F       F
Bank Sta=247.2889,261.6889
XS Rating Curve= 0 ,0
Exp/Cntr(USF)=0,0
Exp/Cntr=0.3,0.1

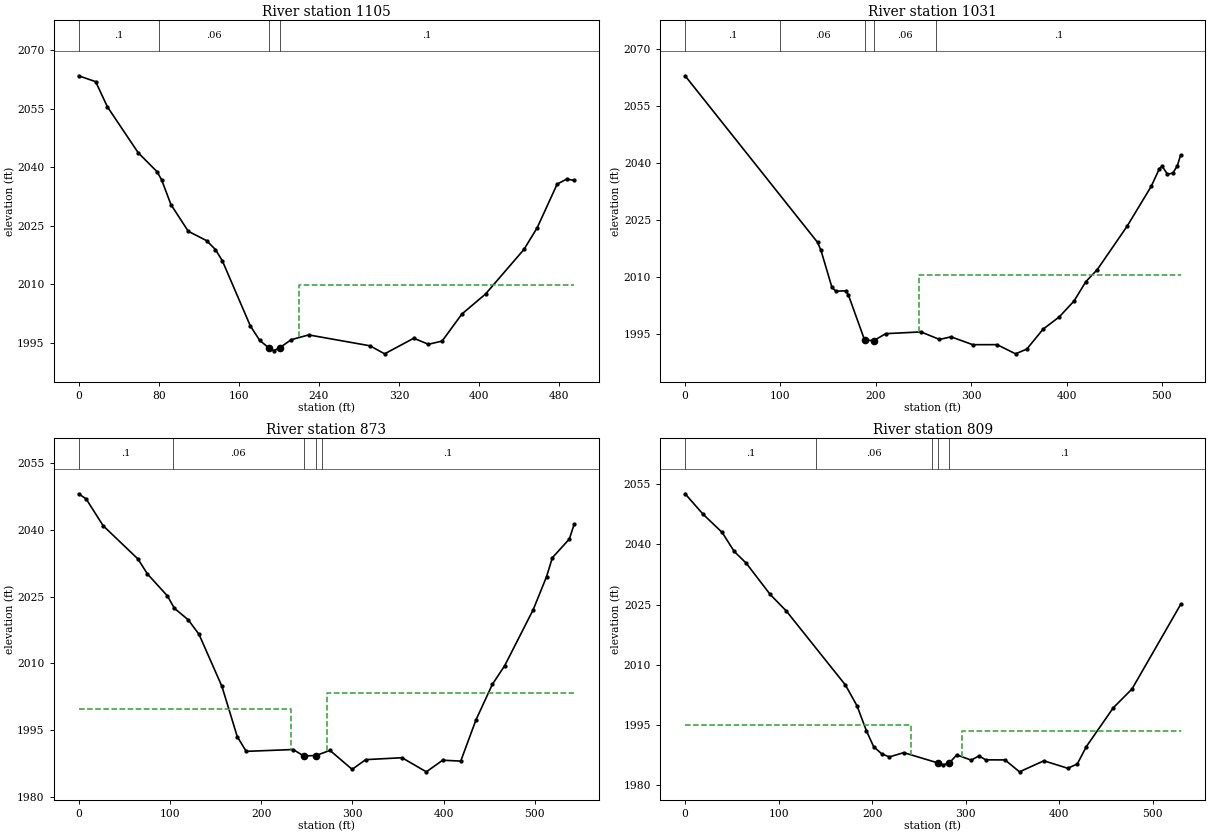
Type RM Length L Ch R = 1 ,1105    ,75.8,74.5,74.2
BEGIN DESCRIPTION:
Structure XS 1
END DESCRIPTION:
XS GIS Cut Line= 4
2185413.11274544631581.4808088282185540.84569953631504.890737298
2185744.30823328631382.2953127922185825.87612502631310.883729819
#Sta/Elev= 30
       0 2063.42      17 2061.91    28.7 2055.48    59.5 2043.69    78.4 2038.81
    82.9 2036.73    92.2  2030.4   109.5 2023.57   127.8 2021.16   136.6 2018.89
   143.5 2016.01   171.5  1999.3   180.8 1995.61190.31881993.594   194.9 1992.97
   200.7 1993.68   212.3 1995.78   229.8    1997     291 1994.21   305.6 1992.15
   334.7 1996.15   349.3  1994.6     363 1995.42   382.8 2002.36   406.4 2007.49
   444.8 2018.93     458 2024.49   477.9 2035.65   487.3 2036.93   494.9 2036.62
#Mann= 4 ,-1,0
       0      .1       0      80     .06       0190.3188    .045       0
   200.7      .1       0
#XS Ineff= 2 , 0
                           220.4         2009.84
Permanent Ineff=
       F       F
Bank Sta=190.3188,200.7
XS Rating Curve= 0 ,0
Exp/Cntr(USF)=0,0
Exp/Cntr=0.3,0.1

Type RM Length L Ch R = 1 ,1031    ,156.7,157.3,155.5
XS GIS Cut Line= 3
 2185452.6180765631659.2621865952185588.45369928631568.590774455
2185858.87052073631336.401313723
#Sta/Elev= 30
       0 2062.94   138.9 2019.08   142.5 2016.96     154 2007.21   158.2 2006.21
   168.4  2006.3   171.2 2005.26   188.2 1993.38 197.6741993.157   210.4 1995.02
   247.3 1995.49   266.8  1993.5   278.9 1994.19   301.7 1992.12   327.2 1992.13
   346.6 1989.71   358.4 1990.97   375.4  1996.2   392.5 1999.46     408 2003.65
   420.3 2008.73   432.2 2011.87   463.5 2023.29   488.9 2033.84   497.4 2038.47
   500.3 2039.15   505.9 2036.98   511.6 2037.35   516.2 2039.21   519.7 2042.09
#Mann= 5 ,-1,0
       0      .1       0     100     .06       0   188.2    .045       0
 197.674     .06       0  263.32      .1       0
#XS Ineff= 2 , 0
                          244.81          2010.4
Permanent Ineff=
       F       F
Bank Sta=188.2,197.674
XS Rating Curve= 0 ,0
Exp/Cntr(USF)=0,0
Exp/Cntr=0.3,0.1

Type RM Length L Ch R = 1 ,873     ,63.8,64.4,64.6
XS GIS Cut Line= 4
2185535.49008431631736.6023400352185537.88275817631738.799793506
2185691.65711852631684.9340509962185914.30200392631380.898353793
#Sta/Elev= 30
       0  2048.1     8.2 2046.96    26.9 2040.92      65 2033.46    75.4 2030.09
    97.3 2025.16   104.9 2022.39   120.1  2019.8   131.9 2016.54     157 2004.86
   173.8 1993.58   183.6 1990.26   235.1 1990.67   246.5 1989.23   260.1 1989.32
   275.4 1990.48   299.7 1986.22   314.6  1988.4   354.3 1988.83     381 1985.66
   398.9 1988.27   418.7 1988.07   435.4 1997.33   453.4 2005.32   466.9 2009.51
   498.1 2022.07   512.7 2029.47   519.1 2033.74   537.7 2037.94     543 2041.26
#Mann= 5 ,-1,0
       0      .1       0  103.25     .06       0   246.5    .045       0
   260.1     .06       0  266.18      .1       0
#XS Ineff= 2 , 0
          232.79 1999.76  272.13         2003.27
Permanent Ineff=
       F       F
Bank Sta=246.5,260.1
XS Rating Curve= 0 ,0
Exp/Cntr(USF)=0,0
Exp/Cntr=0.3,0.1

Type RM Length L Ch R = 1 ,809     ,128.7,129.2,128.4
XS GIS Cut Line= 4
2185555.15826661631793.3931415562185736.18006392631724.252871749
2185889.54575331631535.6884995492185942.34377752631459.005654854
#Sta/Elev= 30
       0 2052.59    19.5 2047.43    39.6 2042.97    52.5 2038.24    65.3 2035.32
      91 2027.51   108.1 2023.43   171.4 2004.97   183.8 1999.79   193.8 1993.61
   201.6 1989.61   210.2 1987.82   218.4 1987.04   233.8 1988.11   270.3 1985.55
   276.2  1985.1   282.5 1985.53   290.5 1987.55     306 1986.24   314.2  1987.3
   321.5 1986.32   342.1  1986.3   357.6 1983.33   383.6 1986.08   409.2 1984.22
   419.4 1985.29   429.1 1989.63   457.8 1999.26   477.9 2003.97   529.9 2025.02
#Mann= 5 ,-1,0
       0      .1       0     140     .06       0  263.78      .1       0
   270.3    .045       0   282.5      .1       0
#XS Ineff= 2 , 0
          241.53 1994.99  296.17         1993.51
Permanent Ineff=
       F       F
Bank Sta=270.3,282.5
XS Rating Curve= 0 ,0
Exp/Cntr(USF)=0,0
Exp/Cntr=0.3,0.1