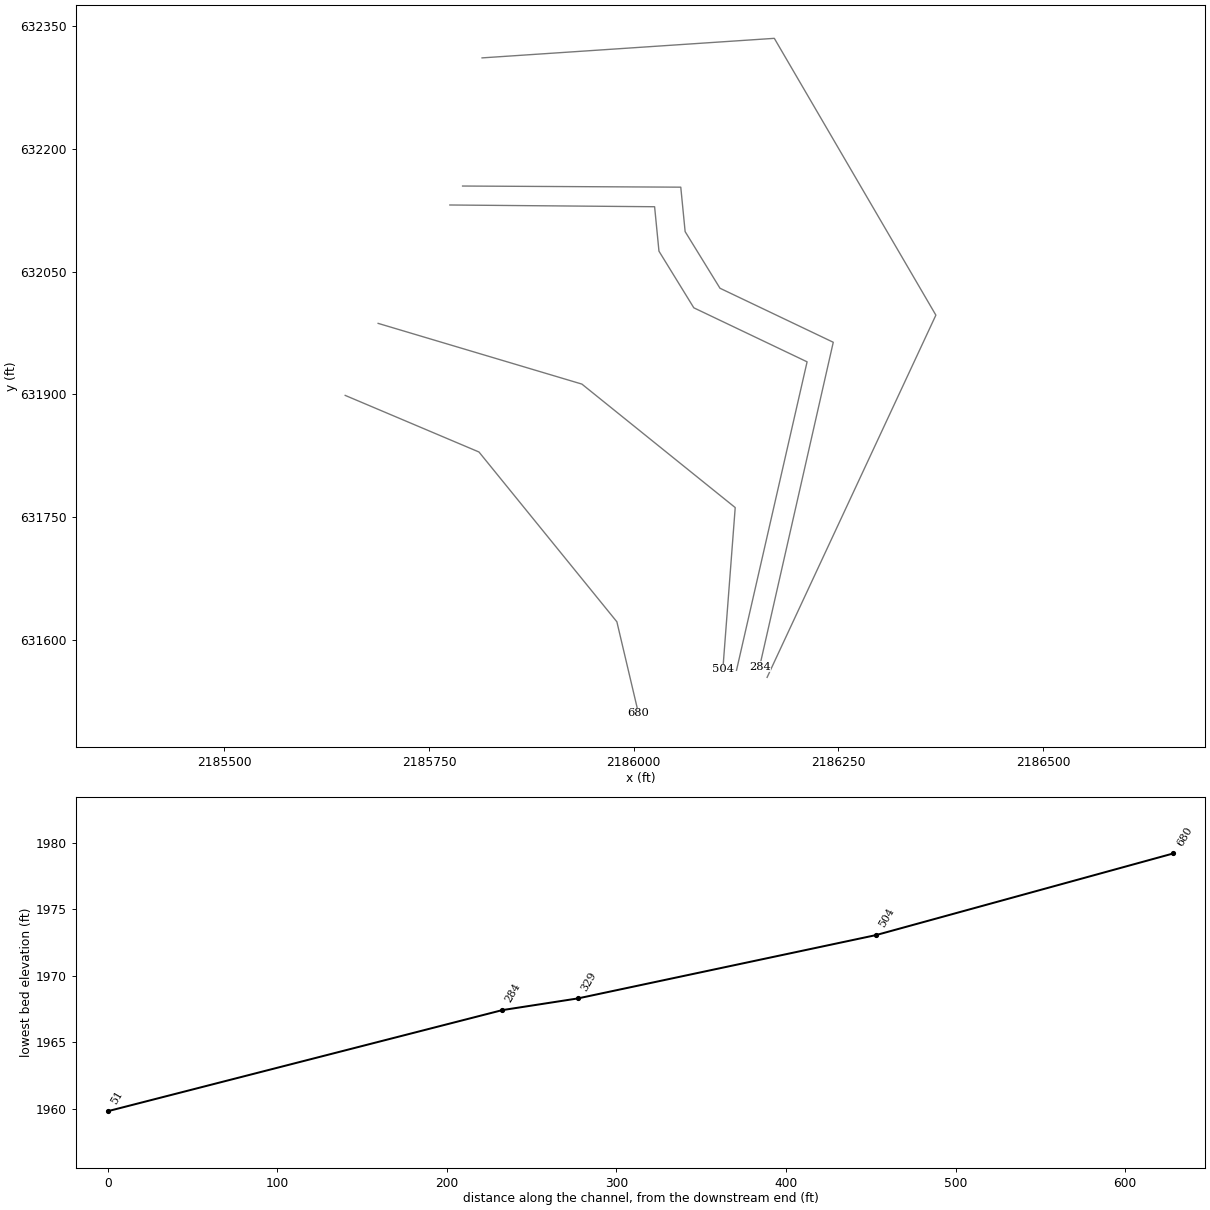
HEC-RAS study SSHANTYRN.prj: SSHANTYRN

--- SSHANTYRN.g01 (geometry) --- (continued)

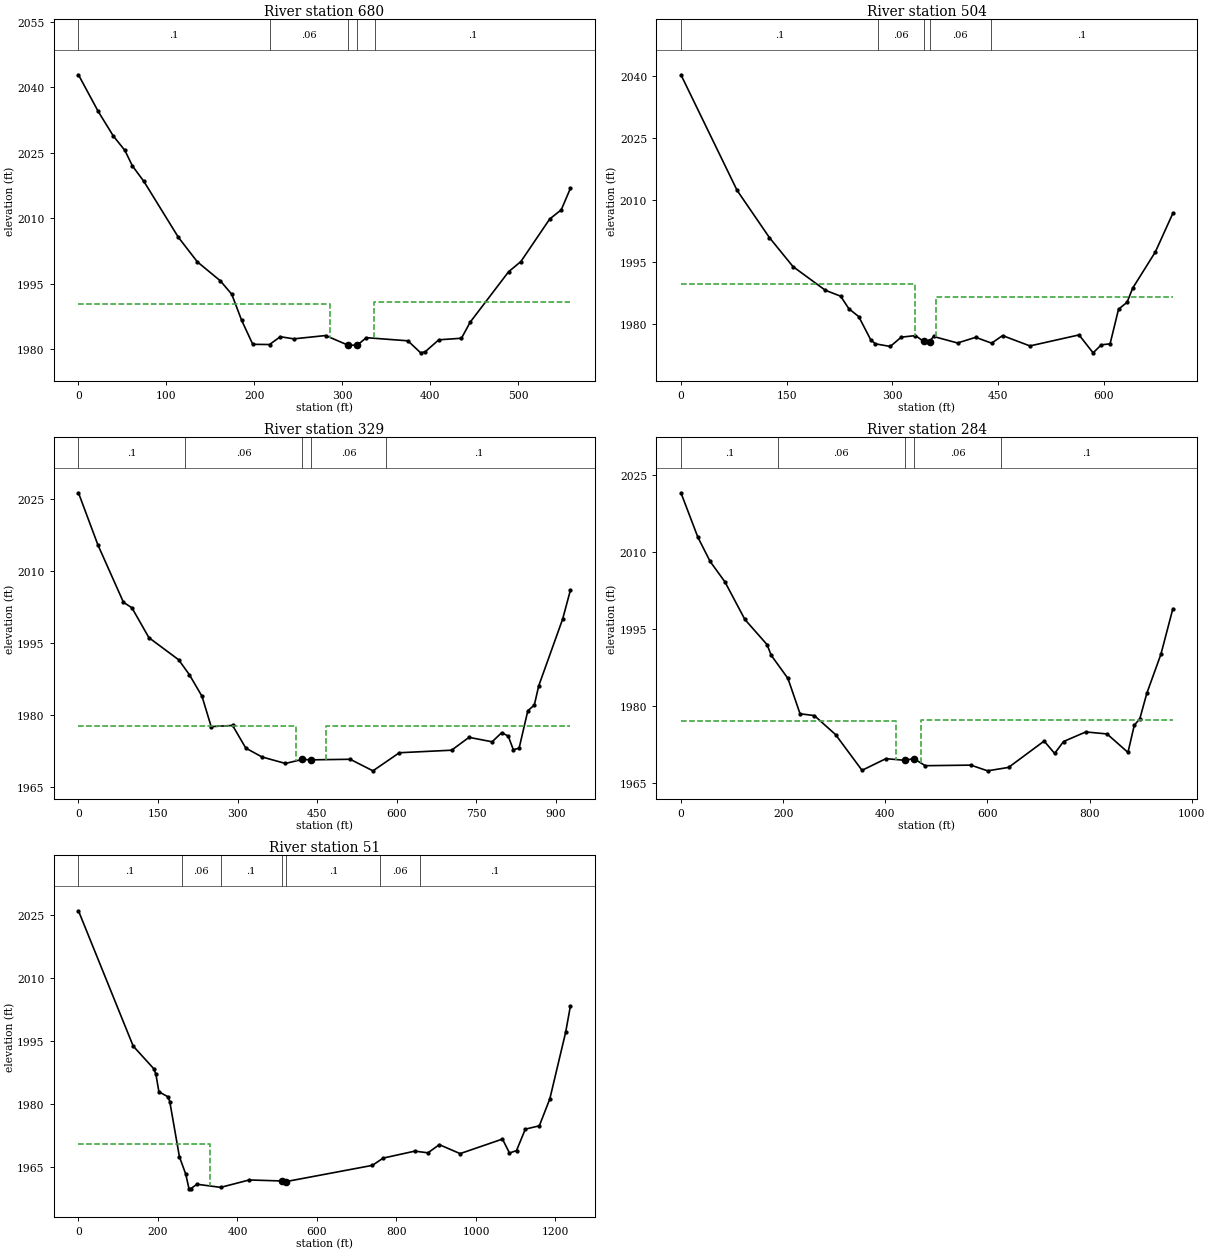
Type RM Length L Ch R = 1 ,680     ,173.5,175.4,175.8
XS GIS Cut Line= 4
2185647.58579516631898.7769170892185811.00825107631829.636647283
2185979.45909023631622.2158378622186005.85810234631510.334310357
#Sta/Elev= 30
       0 2042.83    22.4 2034.47    39.7 2028.81    52.8 2025.53    61.4 2021.97
    74.5 2018.41   113.6 2005.66   135.3 2000.01   161.3  1995.7   174.4 1992.61
   185.6 1986.66   198.3 1981.15   217.4  1981.1   229.6 1982.89     245  1982.4
   281.1 1983.16   306.9 1980.94   317.2 1980.97   327.5 1982.67   374.8 1981.95
   389.3  1979.2   394.5 1979.46   409.9 1982.18   435.7 1982.54   445.7 1986.24
   489.3 1997.75   503.3 2000.09   536.1 2009.83   549.2 2011.92   559.6 2016.82
#Mann= 5 ,-1,0
       0      .1       0  217.45     .06       0   306.9    .045       0
   317.2     .06       0  337.45      .1       0
#XS Ineff= 2 , 0
          286.34 1990.47  336.61          1990.9
Permanent Ineff=
       F       F
Bank Sta=306.9,317.2
XS Rating Curve= 0 ,0
Exp/Cntr(USF)=0,0
Exp/Cntr=0.3,0.1

Type RM Length L Ch R = 1 ,504     ,173.6,175.8,177.8
BEGIN DESCRIPTION:
Structure XS 4
END DESCRIPTION:
XS GIS Cut Line= 4
2185687.81286123631986.7736241162185936.71783253631912.604971051
2186124.02510892 631761.753473292186108.93995914631564.389430387
#Sta/Elev= 30
       0 2040.27    79.7 2012.33   125.6 2000.91   159.1  1993.9   204.9 1988.19
   226.7 1986.75   238.3 1983.73   252.4 1981.81   269.3 1976.23     276 1975.24
   297.1  1974.6   312.7 1976.85   332.9 1977.23   344.3 1975.83   352.8 1975.77
   358.5 1977.02   392.6 1975.44   418.3 1976.81     441  1975.4   456.5 1977.23
   495.3 1974.73     565 1977.39     585 1973.06   596.6 1974.99   609.1 1975.24
   621.1 1983.61   633.2 1985.28   641.2 1988.71   673.3 1997.43   698.2 2006.79
#Mann= 5 ,-1,0
       0      .1       0  279.72     .06       0   344.3    .045       0
   352.8     .06       0  439.72      .1       0
#XS Ineff= 2 , 0
          332.79 1989.63  362.11         1986.46
Permanent Ineff=
       F       F
Bank Sta=344.3,352.8
XS Rating Curve= 0 ,0
Exp/Cntr(USF)=0,0
Exp/Cntr=0.3,0.1

Type RM Length L Ch R = 1 ,329     ,39.8,44.6,40.6
BEGIN DESCRIPTION:
Structure XS 3
END DESCRIPTION:
XS GIS Cut Line= 6
2185775.41677883632131.3938477262186025.55414167632129.264944926
2186030.87639867632074.9779235122186073.45445468632005.788582494
2186211.83313672631939.7925956772186125.61257329631562.976799982
#Sta/Elev= 30
       0 2026.23    36.8 2015.33    84.8 2003.42   100.8 2002.26   132.8 1996.04
   188.8 1991.44   208.8 1988.37   232.8 1983.84   250.1 1977.51   290.4 1977.76
   315.4 1973.03   345.9 1971.19     390 1969.84     422 1970.68     438 1970.59
     512 1970.71     555  1968.3   604.7 1972.07   703.2  1972.6     736 1975.28
   779.5 1974.35   797.6 1976.25   809.9 1975.54   819.5  1972.7   830.4 1973.02
   846.8 1980.81   859.1 1982.02   867.3 1985.99   912.5 1999.94     927 2005.92
#Mann= 5 ,-1,0
       0      .1       0     200     .06       0     422    .045       0
     438     .06       0  580.47      .1       0
#XS Ineff= 2 , 0
          410.11 1977.62  467.15         1977.74
Permanent Ineff=
       F       F
Bank Sta=422,438
XS Rating Curve= 0 ,0
Exp/Cntr(USF)=0,0
Exp/Cntr=0.3,0.1

Type RM Length L Ch R = 1 ,284     ,236.3,232.7,228.5
BEGIN DESCRIPTION:
Structure XS 2
END DESCRIPTION:
XS GIS Cut Line= 6
 2185790.9752266632154.5504045382186057.52431671632153.167489341
2186062.84657371632098.8804679272186105.42462972632029.691126909
2186243.80331176631963.6951400922186153.85281031631567.483666718
#Sta/Elev= 30
       0 2021.46    33.2 2012.81    57.2 2008.11    86.1 2004.15   125.2 1996.84
   168.7 1991.94   176.7 1989.88   209.5 1985.38   233.2 1978.51   261.2 1978.16
   302.7 1974.47   354.6 1967.52   401.4 1969.79   438.1 1969.47   455.8  1969.8
   478.4 1968.42   567.7 1968.53   600.5 1967.42   641.5 1968.09   711.2 1973.21
   731.7  1970.8   749.2 1973.12   792.7 1974.98   834.3 1974.59   875.3    1971
   887.6 1976.27   898.5 1977.55   912.2 1982.49   939.8 1990.08   963.2 1998.93
#Mann= 5 ,-1,0
       0      .1       0     190     .06       0   438.1    .045       0
   455.8     .06       0  626.87      .1       0
#XS Ineff= 2 , 0
          421.66 1977.02  469.31         1977.38
Permanent Ineff=
       F       F
Bank Sta=438.1,455.8
XS Rating Curve= 0 ,0
Exp/Cntr(USF)=0,0
Exp/Cntr=0.3,0.1

Type RM Length L Ch R = 1 ,51      ,,,
BEGIN DESCRIPTION:
Structure XS 1
END DESCRIPTION:
XS GIS Cut Line= 4
2185814.77953851632311.1043443012186171.79474988632334.989164779
2186369.15879278631996.8303906332186162.99507918 631554.33266387
#Sta/Elev= 30
       0  2025.9   137.7 1993.75   189.8 1988.33   194.9 1987.03   202.4 1982.88
   225.9 1981.66   229.9 1980.46     254 1967.44     270 1963.29     278 1959.87
     282 1959.82   298.1 1960.91   357.8 1960.17   429.6 1961.93   511.5 1961.69
  523.321961.563   739.5  1965.4   766.6 1967.13   846.1 1968.78   879.3 1968.38
   907.8 1970.32   960.1 1968.19  1066.7 1971.65  1084.3 1968.33    1102 1968.91
  1124.1    1974  1159.4  1974.8  1185.8  1981.2  1225.6 1997.02  1237.5 2003.23
#Mann= 7 ,-1,0
       0      .1       0     260     .06       0  357.81      .1       0
   511.5    .045       0  523.32      .1       0  759.35     .06       0
  859.35      .1       0
#XS Ineff= 2 , 0
          331.51 1970.47
Permanent Ineff=
       F       F
Bank Sta=511.5,523.32
XS Rating Curve= 0 ,0
Exp/Cntr(USF)=0,0
Exp/Cntr=0.3,0.1
LCMann Table=0

Chan Stop Cuts=-1
Use User Specified Reach Order=0
Composite Channel Slope=5